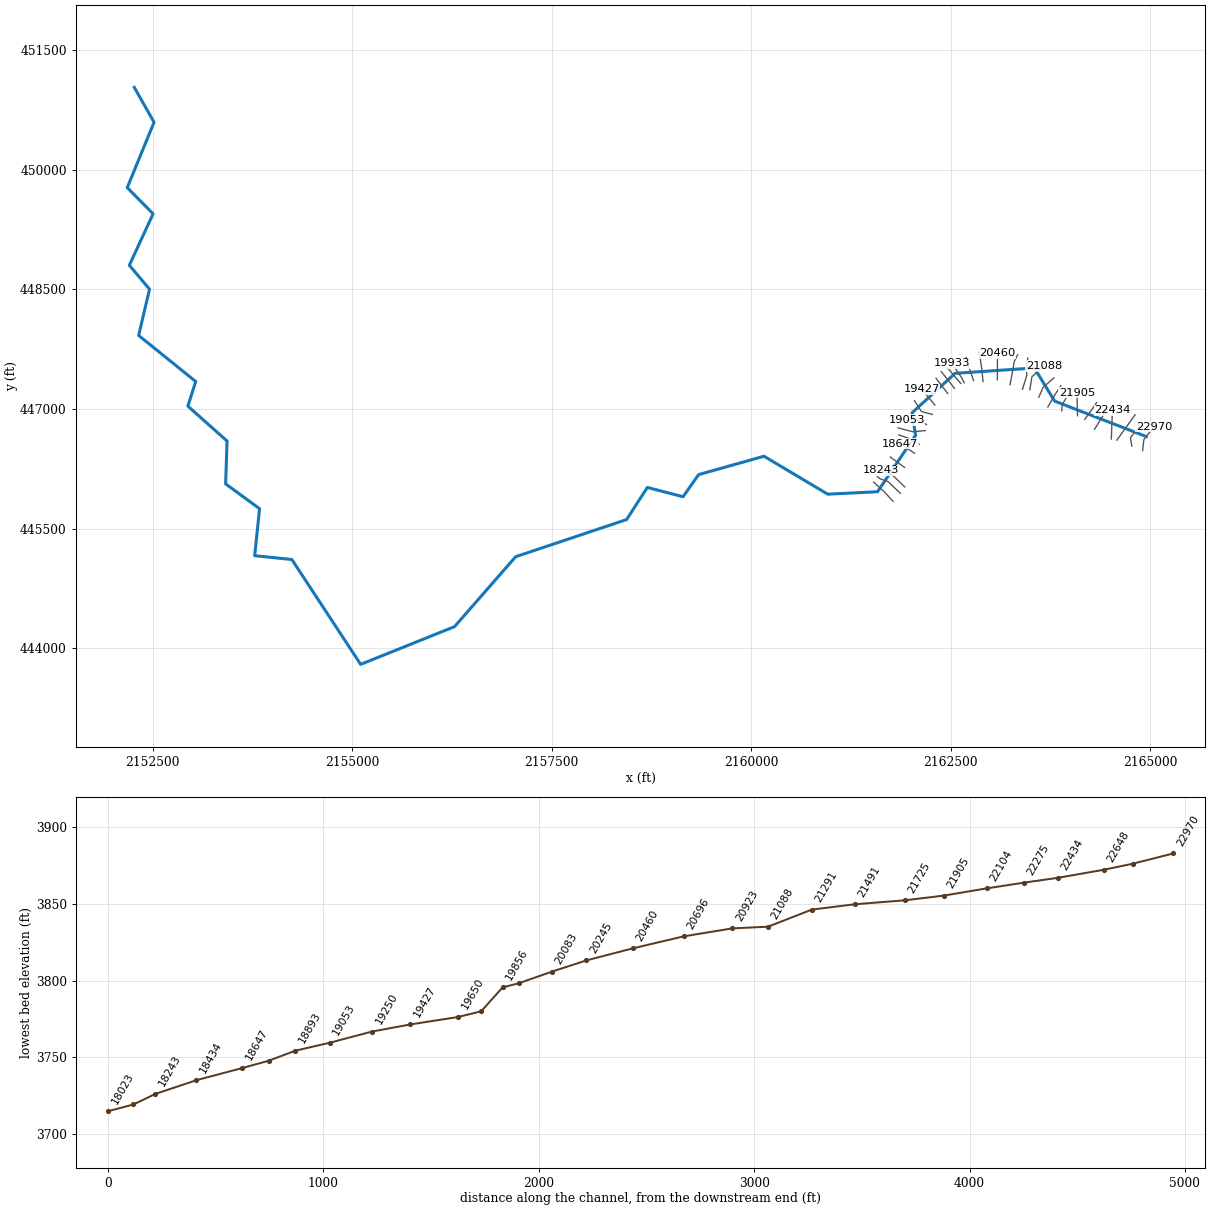
--- DOGWAYFK.prj (project) ---

Proj Title=DOGWAYFK
Current Plan=p01
Default Exp/Contr=0,0
English Units
Geom File=g01
Flow File=f01
Plan File=p01
Background Map Layer=Inundation Boundary (01pct Value_0)
BEGIN DESCRIPTION:
----------MODEL BY WOOD PLC 2021----------
Stream Name: Dogway Fork
Flood Zone: Enhanced Approximate
Pocahontas County, WV
HEC-RAS Version: RAS 6.1
Vertical Datum: NAVD88
Projection: NAD 1983 StatePlane West Virginia S FIPS 4702 (US Feet)
Terrain: 1-meter LIDAR (FEMA Region III 3DEP collected 2016-2018)
Land Use: 2019 NLCD
Hydrologic Method:
WV SIR2010-5033 regression equations
Model Notes:
None
END DESCRIPTION:
DSS File=dss
DSS Export Rating Curves= 0
DSS Export Rating Curve Sorted= 0
DSS Export Volume Flow Curves= 0
DXF OffsetX= 0
DXF OffsetY= 0
DXF ScaleX= 0
DXF ScaleY= 0

--- DOGWAYFK.p01 (plan) ---

Plan Title=Floodplain
Program Version=6.00
Short Identifier=Floodplain
Geom File=g01
Flow File=f01
Subcritical Flow
K Sum by GR= 0
Std Step Tol= 0.01
Critical Tol= 0.01
Num of Std Step Trials= 20
Max Error Tol= 0.3
Flow Tol Ratio= 0.001
Split Flow NTrial= 30
Split Flow Tol= 0.02
Split Flow Ratio= 0.02
Log Output Level= 0
Friction Slope Method= 1
Unsteady Friction Slope Method= 2
Unsteady Bridges Friction Slope Method= 1
Parabolic Critical Depth
Global Vel Dist= 0 , 0 , 0
Global Log Level= 0
CheckData=True
Encroach Param=-1 ,0,0, 0
Computation Interval=0.1SEC
Output Interval=1SEC
Instantaneous Interval=Max Profile
Mapping Interval=1HOUR
Computation Time Step Use Courant=        0
Computation Time Step Use Time Series=    0
Computation Time Step Count To Double=0
Computation Time Step Max Doubling=0
Computation Time Step Max Halving=0
Computation Time Step Residence Courant=0
Run HTab= 0
Run UNet= 0
Run Sediment= 0
Run PostProcess= 0
Run WQNet= 0
Run RASMapper=-1
UNET Theta= 0
UNET Theta Warmup= 0
UNET ZTol= 0
UNET ZSATol= 0
UNET MxIter= 0
UNET Max Iter WO Improvement= 0
UNET MaxInSteps= 0
UNET DtIC= 0
UNET DtMin= 0
UNET MaxCRTS= 0
UNET WFStab= 0
UNET SFStab= 0
UNET WFX= 1
UNET SFX= 1
UNET Gravity=32.174
UNET 1D Methodology=Finite Difference
UNET DSS MLevel= 1
UNET Pardiso=0
UNET DZMax Abort= 0
UNET Use Existing IB Tables= 0
UNET Froude Reduction=False
UNET Froude Limit= 0
UNET Froude Power= 0
UNET D1 Cores= 0
UNET WindReference=Eulerian
UNET WindDragFormulation=Hsu (1988)
UNET D2 Coriolis=0
UNET D2 Cores= 0
UNET D2 Theta= 1
UNET D2 Theta Warmup= 1
UNET D2 Z Tol= 0.01
UNET D2 Volume Tol= 0.01
UNET D2 Max Iterations= 20
UNET D2 Equation= 0
UNET D2 RampUpFraction=0.1
UNET D2 TimeSlices= 1
UNET D2 Turbulence Formulation=Non-Conservative (original)
UNET D2 Eddy Viscosity=0.3
UNET D2 Transverse Eddy Viscosity=0.1
UNET D2 Smagorinsky Mixing=0
UNET D2 BCVolumeCheck=0
UNET D2 Cores=0
UNET D2 SolverType=PARDISO (Direct)
UNET D2 Minimum Iterations= 2147483647
UNET D2 Maximum Iterations= 2147483647
UNET D2 Restart Number= 10
UNET D2 Relaxation Coeff=1.3
UNET D2 SOR Precondition Iterations= 10
UNET D2 ILUT Maximum Fill= 8
UNET D2 ILUT Tolerance=1E-08
UNET D1D2 MaxIter= 0
UNET D1D2 ZTol=0.01
UNET D1D2 QTol=0.1
UNET D1D2 MinQTol=1
DSS File=dss
Write IC File= 0
Write IC File at Fixed DateTime=0
Write IC File at Sim End=0
Echo Input=False
Echo Parameters=False
Echo Output=False
Write Detailed= 0
HDF Write Warmup=0
HDF Write Time Slices=0
HDF Flush=0
HDF Compression= 1
HDF Chunk Size= 1
HDF Spatial Parts= 1
HDF Use Max Rows=0
HDF Fixed Rows= 1
Calibration Method= 0
Calibration Iterations= 20
Calibration Max Change=0.05
Calibration Tolerance=0.2
Calibration Maximum=1.5
Calibration Minimum=0.5
Calibration Optimization Method= 1
WQ AD Non Conservative
WQ ULTIMATE=-1
WQ Max Comp Step=1HOUR
WQ Output Interval=15MIN
WQ Output Selected Increments= 0
WQ Output face flow=0
WQ Output face velocity=0
WQ Output face area=0
WQ Output face dispersion=0
WQ Output cell volume=0
WQ Output cell surface area=0
WQ Output cell continuity=0
WQ Output cumulative cell continuity=0
WQ Output face conc=0
WQ Output face dconc_dx=0
WQ Output face courant=0
WQ Output face peclet=0
WQ Output face adv mass=0
WQ Output face disp mass=0
WQ Output cell mass=0
WQ Output cell source sink temp=0
WQ Output nsm pathways=0
WQ Output nsm derived pathways=0
WQ Create Restart=0
WQ Fixed Restart=0
WQ System Summary=0
WQ Write To DSS=0
Sorting and Armoring Iterations= 10
XS Update Threshold= 0.02
Bed Roughness Predictor= 0
Hydraulics Update Threshold= 0.02
Energy Slope Method= 1
Volume Change Method= 1
Sediment Retention Method= 0
Sediment TS Multiplier= 1
Warm Up Method= 0
XS Weighting Method= 0
Number of US Weighted Cross Sections= 1
Number of DS Weighted Cross Sections= 1
Upstream XS Weight=0
Main XS Weight=1
Downstream XS Weight=0
Number of DS XS's Weighted with US Boundary= 1
Upstream Boundary Weight= 1
Weight of XSs Associated with US Boundary= 0
Number of US XS's Weighted with DS Boundary= 1
Downstream Boundary Weight= 0.5
Weight of XSs Associated with DS Boundary= 0.5
Percentile Method= 0
Sediment Output Level= 3
Mass or Volume Output= 0
Output Increment Type= 1
Profile and TS Output Increment= 1
Transport Output Increment 1
XS Output Flag= 0
XS Output Increment= 10
Read HDF5 Sediment Hotstart= 0
Sediment Hotstart Type= 0
Write Gradation File= 0
Read Gradation Hotstart= 0
Write HDF5 File= 1
Write Binary Output= 1
Write DSS Sediment File= 0
DSS Sediment Output Type= 1
SV Curve= 0
Specific Gage Flag= 0
Subcell Erosion Methods= 0
Subcell Deposition Methods= 0
Advection Scheme= 1
Matrix Solver= 0
Implicit Weighting Factor= 1
Maximum Outer Loop Convergence Iterations= 5
Convergence Maximum Absolute= 0.001
Convergence RMSE= 0.0001
Grain Fractions Max Abs Error= 0.001
Max Subgrid Regions= 1
Max Subgrid Length Scale= 3.402823E+38
Initial Layer Thickness= 3.402823E+38
Min Layer Thickness= 3.402823E+38
Max Layer Thickness= 3.402823E+38
Number of Layers= 5

--- DOGWAYFK.f01 (steady flow) ---

Flow Title=Flow
Program Version=6.00
Number of Profiles= 6
Profile Names=01pct,10pct,04pct,02pct,0_2pct,01plus
River Rch & RM=DOGWAYFK,Main            ,22970
     629     333     443     533     877     930
River Rch & RM=DOGWAYFK,Main            ,18142
     766     409     542     650    1060    1130
River Rch & RM=DOGWAYFK,Main            ,17525
     858     461     608     729    1190    1270
River Rch & RM=DOGWAYFK,Main            ,14244
     969     523     688     824    1340    1430
River Rch & RM=DOGWAYFK,Main            ,10893
    1130     615     807     965    1560    1680
River Rch & RM=DOGWAYFK,Main            ,6193
    1260     686     899    1070    1730    1860
Boundary for River Rch & Prof#=DOGWAYFK,Main            , 1
Up Type= 0
Dn Type= 3
Dn Slope=0.01367
Boundary for River Rch & Prof#=DOGWAYFK,Main            , 2
Up Type= 0
Dn Type= 3
Dn Slope=0.01367
Boundary for River Rch & Prof#=DOGWAYFK,Main            , 3
Up Type= 0
Dn Type= 3
Dn Slope=0.01367
Boundary for River Rch & Prof#=DOGWAYFK,Main            , 4
Up Type= 0
Dn Type= 3
Dn Slope=0.01367
Boundary for River Rch & Prof#=DOGWAYFK,Main            , 5
Up Type= 0
Dn Type= 3
Dn Slope=0.01367
Boundary for River Rch & Prof#=DOGWAYFK,Main            , 6
Up Type= 0
Dn Type= 3
Dn Slope=0.01367
DSS Import GetInterval= 0
DSS Import GetPeak= 0
DSS Import FillOption= 0

--- DOGWAYFK.g01 (geometry) ---

Geom Title=Geometry
Program Version=6.10

River Reach=DOGWAYFK        ,Main
Reach XY= 30
     2164950.613      446653.3372163801.95724634 447098.07869053
     2163547.514      447513.5232162554.25117447447446.067857559
     2162015.379       446951.06  2162059.234706446669.635125486
      2161582.75      445961.473     2160958.739      445931.088
       2160159.6      446406.859     2159340.716      446176.299
     2159145.969       445898.73     2158698.145      446015.393
2158437.84222639445612.6084367872157048.26746492445146.843958986
     2156282.363      444270.307     2155105.722       443797.42
     2154243.996      445111.7982153778.13375967445160.178939917
 2153839.1837025445748.6549150822153414.04812147446060.335261326
       2153431.9      446597.334     2152940.849      447035.086
2153039.33855612447343.475911883 2152323.8537746447921.465174876
2152460.55023467448501.096382666     2152207.493      448800.901
     2152505.102      449446.061     2152181.381      449774.565
     2152517.157      450593.991 2152269.1921891 451031.64532569

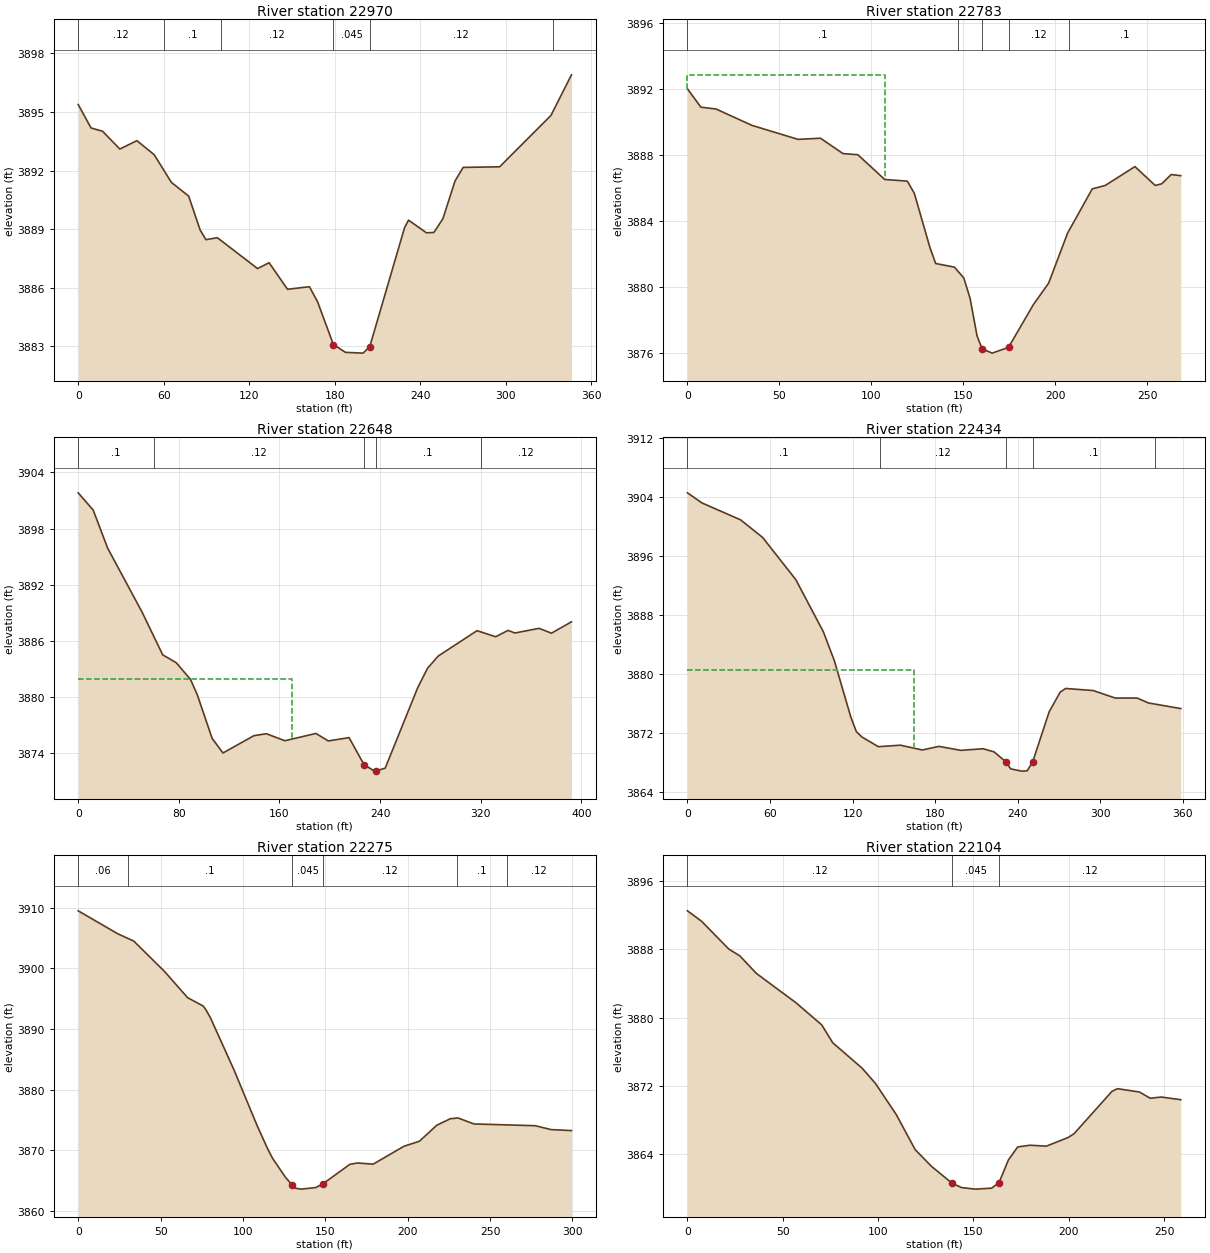
Type RM Length L Ch R = 1 ,22970   ,187.9,187.3,185.3
XS GIS Cut Line= 3
2164903.98295056446476.2089429412164920.44688453446618.055543548
2165047.78889073446776.363821809
#Sta/Elev= 30
       0 3895.38       9 3894.18    17.1 3894.01    29.2  3893.1    41.2 3893.53
    53.3 3892.81    65.4 3891.39    77.5 3890.69    85.5 3888.96    89.6 3888.46
    97.6 3888.56   125.8 3886.98   133.9 3887.28   146.8 3885.92   162.2 3886.05
   167.9 3885.28     179 3883.09   187.5 3882.69   199.8 3882.65 204.4753882.975
   228.9 3889.07   231.7 3889.46   244.3 3888.81   249.5 3888.83   255.8 3889.53
   264.3 3891.46     270 3892.16   295.6 3892.19   331.6 3894.82     346  3896.9
#Mann= 6 ,-1,0
       0     .12       0      60      .1       0     100     .12       0
     179    .045       0 204.475     .12       0   332.8      .1       0
Bank Sta=179,204.475
XS Rating Curve= 0 ,0
Exp/Cntr(USF)=0,0
Exp/Cntr=0.3,0.1

Type RM Length L Ch R = 1 ,22783   ,135.8,134.6,134.3
XS GIS Cut Line= 3
2164769.39757165446533.9442598392164751.18560027446639.602015659
2164851.75855863446765.237322599
#Sta/Elev= 30
       0 3892.01     7.3  3890.9    15.5 3890.79      35  3889.8    60.1 3888.95
    72.3 3889.02    84.5 3888.09    92.6 3888.02   107.2 3886.52   119.5 3886.42
   123.3 3885.68   131.8 3882.39   134.9 3881.43   145.1 3881.21   150.2 3880.55
   153.6 3879.32   157.4 3877.04160.10583876.266   165.6    3876   174.5 3876.35
     188 3878.94   196.3 3880.24   206.6 3883.27     220 3885.95   227.1 3886.16
   243.2  3887.3   254.2 3886.16   257.8 3886.26   262.9 3886.82   268.1 3886.75
#Mann= 5 ,-1,0
       0      .1       0  147.22     .12       0160.1058    .045       0
   174.5     .12       0  207.22      .1       0
#XS Ineff= 2 , 0
          107.19 3892.86
Permanent Ineff=
       F       F
Bank Sta=160.1058,174.5
XS Rating Curve= 0 ,0
Exp/Cntr(USF)=0,0
Exp/Cntr=0.3,0.1

Type RM Length L Ch R = 1 ,22648   ,206.4,213.7,218.3
XS GIS Cut Line= 2
2164580.88731997446607.7970331552164809.98936574446926.067103774
#Sta/Elev= 30
       0 3901.82    11.9 3899.98    23.4 3895.91      51 3889.01    67.2 3884.49
    77.9 3883.66    89.3 3881.86    94.6 3880.26   106.5 3875.56   115.1    3874
   139.7 3875.85   149.6 3876.06   164.3 3875.31     189 3876.09   198.8 3875.29
   215.4 3875.64227.19833872.766   235.5 3872.06236.4926 3872.06   244.1 3872.38
   269.9 3880.97   277.7 3883.05   286.3 3884.37   317.1 3887.08   331.9 3886.43
   341.8 3887.11   347.2 3886.83   366.4 3887.33   376.3 3886.81   392.2 3888.03
#Mann= 5 ,-1,0
       0      .1       0      60     .12       0227.1983    .045       0
236.4926      .1       0     320     .12       0
#XS Ineff= 2 , 0
          169.59 3881.92
Permanent Ineff=
       F       F
Bank Sta=227.1983,236.4926
XS Rating Curve= 0 ,0
Exp/Cntr(USF)=0,0
Exp/Cntr=0.3,0.1

Type RM Length L Ch R = 1 ,22434   ,158.7,159.8,147.3
XS GIS Cut Line= 2
2164511.92413143446622.5862465042164525.66410031446980.714629957
#Sta/Elev= 30
       0 3904.58    10.5 3903.21    38.6 3900.91    54.6 3898.52    78.7  3892.8
    98.7 3885.73   106.7  3881.8   118.7 3874.13   122.7 3872.16   126.7 3871.44
   138.7 3870.12   154.7 3870.32   170.7 3869.67   182.7 3870.16   198.7 3869.62
   214.8 3869.84   222.8 3869.41   231.4 3868.05   234.8 3867.11   242.8  3866.8
   246.8 3866.84   250.8 3868.04   262.8 3874.86   270.8 3877.52   274.8 3878.02
   294.8 3877.74   310.8 3876.72   326.8 3876.72   334.8 3876.06   358.4 3875.29
#Mann= 5 ,-1,0
       0      .1       0     140     .12       0   231.4    .045       0
   250.8      .1       0     340     .12       0
#XS Ineff= 2 , 0
          164.67 3880.53
Permanent Ineff=
       F       F
Bank Sta=231.4,250.8
XS Rating Curve= 0 ,0
Exp/Cntr(USF)=0,0
Exp/Cntr=0.3,0.1

Type RM Length L Ch R = 1 ,22275   ,170.2,171,170.8
XS GIS Cut Line= 2
2164302.56263566446744.5220936972164458.80135972 446999.91231573
#Sta/Elev= 30
       0 3909.48    24.2 3905.67    33.7  3904.5    52.4 3899.49    66.4 3895.17
    75.8  3893.8    77.3 3893.28    80.2 3891.89    94.6 3883.24   108.6 3874.09
   115.1  3870.2     118 3868.69   125.7 3865.61     130 3864.25   132.1 3863.76
   135.5 3863.62   144.2 3863.88   148.7 3864.52   164.9 3867.71   169.6 3867.93
     179 3867.73   197.7 3870.68   207.1 3871.51   217.7 3874.16   225.8 3875.21
   230.5 3875.35   240.2 3874.36   277.4 3874.07     287 3873.43   299.4 3873.27
#Mann= 6 ,-1,0
       0     .06       0      30      .1       0     130    .045       0
   148.7     .12       0     230      .1       0     260     .12       0
Bank Sta=130,148.7
XS Rating Curve= 0 ,0
Exp/Cntr(USF)=0,0
Exp/Cntr=0.3,0.1

Type RM Length L Ch R = 1 ,22104   ,189.4,198.4,206.7
XS GIS Cut Line= 2
2164179.37441091446867.710318443  2164328.602423447079.033208046
#Sta/Elev= 30
       0 3892.51     7.4 3891.29    21.7 3888.03    27.5 3887.23    36.1 3885.19
    56.9 3881.75    70.4 3879.16    76.2 3877.06    91.5 3874.11    98.5 3872.33
   109.5 3868.66   119.4 3864.56   127.9 3862.61   138.9  3860.6   143.8 3860.11
   150.9 3859.93   159.5 3860.04   163.4 3860.69   168.3 3863.34   173.2 3864.87
   179.6 3865.07   188.2 3864.96   199.7 3865.98   202.8 3866.43   222.6 3871.37
   225.5 3871.69     237  3871.3   242.7 3870.57   248.5 3870.71   258.7  3870.4
#Mann= 3 ,-1,0
       0     .12       0   138.9    .045       0   163.4     .12       0
Bank Sta=138.9,163.4
XS Rating Curve= 0 ,0
Exp/Cntr(USF)=0,0
Exp/Cntr=0.3,0.1

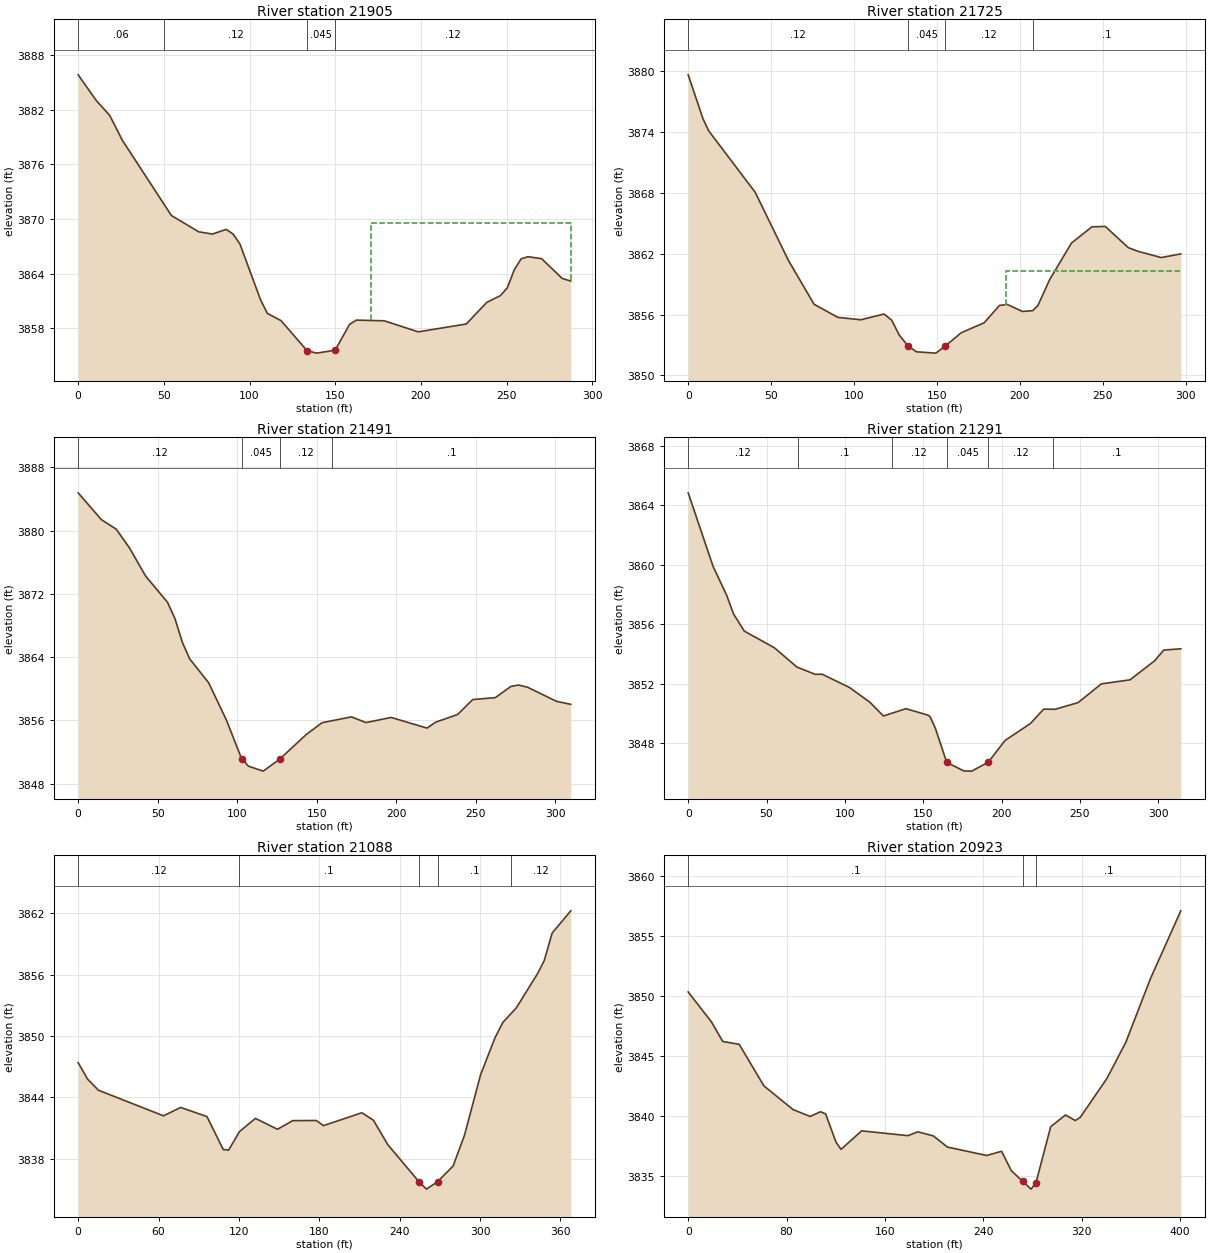
Type RM Length L Ch R = 1 ,21905   ,187,180.5,172.6
XS GIS Cut Line= 2
2164088.23515521446914.7822417192164081.22444323447202.221432792
#Sta/Elev= 30
       0 3885.84    10.6 3883.01    18.4 3881.38    25.8 3878.64    54.4 3870.38
    70.4 3868.58    78.4 3868.34    86.4 3868.85    90.4 3868.34    94.4 3867.25
   106.4 3861.14   110.4 3859.62   118.4 3858.82   133.6 3855.52   139.1 3855.25
     150 3855.57   158.4 3858.41   162.4 3858.88   178.7  3858.8   198.5 3857.59
   226.5 3858.45   238.5 3860.83   246.5 3861.58   250.5 3862.44   254.5  3864.4
   258.5 3865.61   262.5 3865.85   270.5 3865.63   282.5 3863.46   287.5 3863.17
#Mann= 4 ,-1,0
       0     .06       0      50     .12       0   133.6    .045       0
     150     .12       0
#XS Ineff= 2 , 0
                          170.81          3869.5
Permanent Ineff=
       F       F
Bank Sta=133.6,150
XS Rating Curve= 0 ,0
Exp/Cntr(USF)=0,0
Exp/Cntr=0.3,0.1

Type RM Length L Ch R = 1 ,21725   ,230.9,233.6,231.3
XS GIS Cut Line= 3
2163890.81088841446976.9397215562163896.95200428447054.471309318
2164008.25972928447243.310622084
#Sta/Elev= 30
       0 3879.65     8.9 3875.33    12.3 3874.14    40.4 3868.06    60.4 3861.35
    75.9 3857.01    90.2 3855.72   104.1 3855.48   118.1 3856.05   122.7 3855.44
   127.3 3853.96   132.53852.913   137.6 3852.32   149.3 3852.19     155 3852.88
   164.5 3854.19   178.5 3855.19   187.7  3856.9   192.4 3856.99   201.6  3856.3
   207.7 3856.38   210.9  3856.9     218 3859.46   231.1 3863.05   243.4 3864.65
   251.5 3864.69   265.3  3862.6   271.3 3862.23   285.2 3861.62     297 3861.98
#Mann= 4 ,-1,0
       0     .12       0   132.5    .045       0     155     .12       0
  207.77      .1       0
#XS Ineff= 2 , 0
                          191.71         3860.33
Permanent Ineff=
       F       F
Bank Sta=132.5,155
XS Rating Curve= 0 ,0
Exp/Cntr(USF)=0,0
Exp/Cntr=0.3,0.1

Type RM Length L Ch R = 1 ,21491   ,205.9,200,198.7
XS GIS Cut Line= 3
2163716.55672582447024.5333694892163807.90582427447181.899463461
2163878.52865669447288.601351568
#Sta/Elev= 30
       0 3884.79    14.6  3881.4    23.9  3880.2    32.4 3877.79    42.4 3874.27
    56.2 3870.95    60.9 3868.87    65.5 3865.91    70.1 3863.81    82.1 3860.76
    93.2 3856.08   102.8 3851.18   107.1 3850.22   116.4 3849.59   126.7 3851.09
   143.6 3854.24   153.4 3855.71   171.9 3856.45   181.1 3855.73   196.9 3856.38
   219.5 3855.03   224.9 3855.78   238.7 3856.75   248.2 3858.64   262.5 3858.89
   272.2  3860.3     277 3860.48   282.7  3860.2     301 3858.41   309.9 3858.04
#Mann= 4 ,-1,0
       0     .12       0   102.8    .045       0   126.7     .12       0
     160      .1       0
Bank Sta=102.8,126.7
XS Rating Curve= 0 ,0
Exp/Cntr(USF)=0,0
Exp/Cntr=0.3,0.1

Type RM Length L Ch R = 1 ,21291   ,202,203.4,200.8
XS GIS Cut Line= 3
2163603.71372185447146.5880472522163655.91320668447268.642725016
2163792.55303462447388.394484331
#Sta/Elev= 30
       0 3864.84    15.9 3859.89    24.6 3857.94    28.9  3856.7    35.8 3855.54
      55 3854.42    69.4 3853.12    81.1 3852.63    85.5 3852.64   102.9 3851.75
   115.9 3850.76   124.6 3849.83     139 3850.32   153.2 3849.88   154.4 3849.78
   157.8 3848.99     165 3846.71     176 3846.13     181 3846.12   191.6 3846.73
   202.2 3848.18   218.4 3849.32   226.9 3850.29   234.2 3850.28   248.9 3850.73
   263.7 3851.99     282 3852.26   297.7 3853.54   303.5 3854.26   314.4 3854.35
#Mann= 6 ,-1,0
       0     .12       0      70      .1       0     130     .12       0
     165    .045       0   191.6     .12       0  232.75      .1       0
Bank Sta=165,191.6
XS Rating Curve= 0 ,0
Exp/Cntr(USF)=0,0
Exp/Cntr=0.3,0.1

Type RM Length L Ch R = 1 ,21088   ,151.3,164.9,171.3
XS GIS Cut Line= 3
2163491.32310685447242.2826440912163517.36289419 447403.52901957
2163670.59702741447538.735607705
#Sta/Elev= 30
       0 3847.39       7 3845.78    15.1 3844.69    63.7 3842.18    76.5    3843
    96.1 3842.11   108.3 3838.88   112.3 3838.82   120.4 3840.63   132.3 3841.93
   148.8 3840.86   160.2 3841.71   177.8 3841.72   183.1 3841.22   211.8 3842.48
   220.4 3841.75   231.1 3839.36   254.3 3835.74     260    3835   268.4 3835.74
   279.9 3837.27   288.4 3840.29   300.4 3846.21   311.1 3849.81     317 3851.33
   327.1 3852.76   343.1 3856.15   347.9 3857.39   353.8 3860.08   367.7 3862.26
#Mann= 5 ,-1,0
       0     .12       0     120      .1       0   254.3    .045       0
   268.4      .1       0  323.34     .12       0
Bank Sta=254.3,268.4
XS Rating Curve= 0 ,0
Exp/Cntr(USF)=0,0
Exp/Cntr=0.3,0.1

Type RM Length L Ch R = 1 ,20923   ,229.7,227.2,219.4
XS GIS Cut Line= 4
2163399.18232086447246.2887652212163452.26342583 447419.55350409
2163447.68328498447559.7929517592163466.43839279447636.663855969
#Sta/Elev= 30
       0 3850.33    19.1 3847.81    28.1 3846.21    41.5 3845.97    61.6 3842.51
    85.3 3840.54    99.2 3839.97   107.6 3840.36   111.8 3840.18   120.2 3837.84
   124.3 3837.23   141.1 3838.77   178.7 3838.37   186.8 3838.69   199.4 3838.35
   210.9 3837.42   242.9 3836.72   254.9 3837.07   262.9 3835.45     272 3834.58
   278.9 3833.92   282.9 3834.45   294.9 3839.12   306.9 3840.09   314.9 3839.63
   318.9 3839.89   340.5 3843.11   355.9 3846.12     376 3851.43   400.7 3857.08
#Mann= 3 ,-1,0
       0      .1       0     272    .045       0   282.9      .1       0
Bank Sta=272,282.9
XS Rating Curve= 0 ,0
Exp/Cntr(USF)=0,0
Exp/Cntr=0.3,0.1

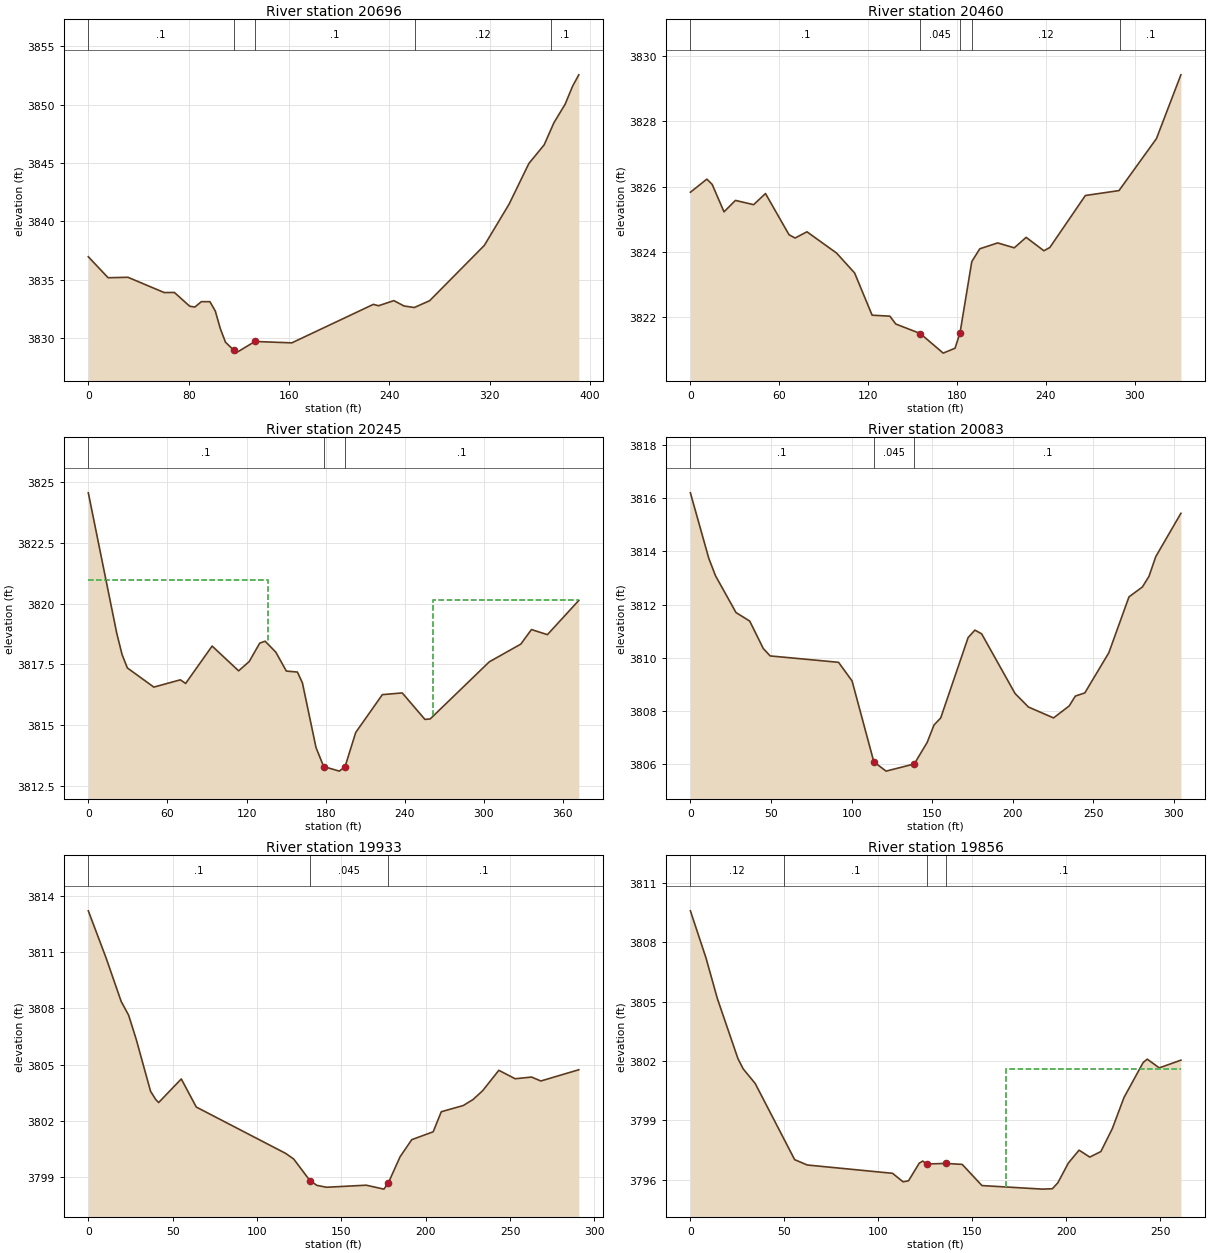
Type RM Length L Ch R = 1 ,20696   ,226.8,235.8,235.2
XS GIS Cut Line= 3
2163242.92316494447301.6512227762163296.65792873447595.657144684
2163338.11046081447677.794569343
#Sta/Elev= 30
       0 3836.97    15.8 3835.17    31.6 3835.21    60.5  3833.9    68.6 3833.91
    80.8 3832.73    84.9 3832.66    90.1 3833.12    96.9 3833.12   101.2 3832.32
   105.2 3830.81   109.3 3829.65   115.93828.963   117.4 3828.71   132.83829.709
   162.2 3829.59   227.2 3832.89   231.3 3832.77   243.5 3833.21   251.6 3832.75
   259.8 3832.62     272  3833.2   315.6 3837.94   335.4 3841.49   351.1 3844.96
   363.3 3846.56   371.1 3848.46     380 3850.04     386  3851.6   390.9 3852.56
#Mann= 5 ,-1,0
       0      .1       0   115.9    .045       0   132.8      .1       0
     260     .12       0  368.88      .1       0
Bank Sta=115.9,132.8
XS Rating Curve= 0 ,0
Exp/Cntr(USF)=0,0
Exp/Cntr=0.3,0.1

Type RM Length L Ch R = 1 ,20460   ,205.2,214.9,209.4
XS GIS Cut Line= 2
2163083.70028188447366.4723991192163085.70334244447697.683141177
#Sta/Elev= 30
       0 3825.83    11.1 3826.23    14.7 3826.07    22.7 3825.23    30.4 3825.58
    42.7 3825.45    50.7 3825.79    66.6 3824.53    70.7 3824.43    78.7 3824.62
    98.7 3823.97   110.9 3823.36   122.7 3822.07   134.7 3822.04   138.7  3821.8
   155.2 3821.51   170.7 3820.91   178.7 3821.06   182.1 3821.54     190 3823.71
   195.4  3824.1   207.5 3824.28   218.7 3824.13   226.7 3824.45   238.7 3824.04
   242.7 3824.14   266.7 3825.73   289.4 3825.88   314.7 3827.47   331.2 3829.42
#Mann= 5 ,-1,0
       0      .1       0   155.2    .045       0   182.1      .1       0
     190     .12       0     290      .1       0
Bank Sta=155.2,182.1
XS Rating Curve= 0 ,0
Exp/Cntr(USF)=0,0
Exp/Cntr=0.3,0.1

Type RM Length L Ch R = 1 ,20245   ,156.4,161.5,159.8
XS GIS Cut Line= 3
2162904.35438221447343.6710934212162891.40646764447480.646851322
2162858.25716349447712.663750483
#Sta/Elev= 30
       0 3824.56    21.6 3818.77    25.6  3817.9    29.6 3817.35    49.7 3816.56
    69.8 3816.86    73.8 3816.71    93.9 3818.25     114 3817.23     122 3817.61
     130 3818.37   134.1 3818.45   142.2    3818   150.2 3817.22   158.6 3817.18
   162.4 3816.73   172.7 3814.07178.4979 3813.29   190.4  3813.1194.6979 3813.28
   202.8 3814.69     223 3816.25   238.1 3816.32   255.3 3815.23   259.3 3815.25
   304.1  3817.6     328 3818.33   336.1 3818.93   348.2 3818.72     372 3820.13
#Mann= 3 ,-1,0
       0      .1       0178.4979    .045       0194.6979      .1       0
#XS Ineff= 2 , 0
           136.3 3820.97  261.75         3820.15
Permanent Ineff=
       F       F
Bank Sta=178.4979,194.6979
XS Rating Curve= 0 ,0
Exp/Cntr(USF)=0,0
Exp/Cntr=0.3,0.1

Type RM Length L Ch R = 1 ,20083   ,149.6,150.1,160.3
XS GIS Cut Line= 3
2162786.24578798447354.454035729 2162728.1570316447521.709592903
2162693.70919949447644.166167714
#Sta/Elev= 30
       0  3816.2    11.4 3813.74    15.6 3813.08    28.3  3811.7    36.8 3811.38
    45.2 3810.35    49.5 3810.07    91.9 3809.83   100.3 3809.13   113.8 3806.09
   121.4 3805.74   138.9 3806.01   146.9 3806.82   151.1 3807.47   155.3 3807.74
   172.3 3810.76   176.5 3811.04   180.7  3810.9   201.4 3808.66   209.7 3808.15
   225.3 3807.74     235 3808.19   238.8 3808.56   244.7 3808.68   259.6 3810.19
   272.1 3812.29   280.4 3812.66   284.5 3813.06   288.7  3813.8   304.3 3815.43
#Mann= 3 ,-1,0
       0      .1       0   113.8    .045       0   138.9      .1       0
Bank Sta=113.8,138.9
XS Rating Curve= 0 ,0
Exp/Cntr(USF)=0,0
Exp/Cntr=0.3,0.1

Type RM Length L Ch R = 1 ,19933   ,76.1,77.7,68.8
XS GIS Cut Line= 3
2162668.03901598447327.685551076 2162636.9606378447391.223568698
2162511.95649443447572.168792797
#Sta/Elev= 30
       0  3813.2    10.6 3810.67    19.5 3808.36    23.9 3807.63    28.4 3806.34
    36.9 3803.57    39.9 3803.14    41.7 3802.97    55.1 3804.23      64 3802.73
   116.9 3800.26   121.7 3799.96   131.4  3798.8   135.5 3798.55   141.2 3798.45
   164.7 3798.56   175.2 3798.35   177.7 3798.66   184.8 3800.08   191.7 3800.99
   204.4 3801.41   209.2 3802.48   222.2 3802.81     228 3803.13   233.7  3803.6
   243.3 3804.69     253 3804.24   262.7 3804.33   268.2 3804.12   290.7 3804.72
#Mann= 3 ,-1,0
       0      .1       0   131.4    .045       0   177.7      .1       0
Bank Sta=131.4,177.7
XS Rating Curve= 0 ,0
Exp/Cntr(USF)=0,0
Exp/Cntr=0.3,0.1

Type RM Length L Ch R = 1 ,19856   ,100.9,99.2,95.4
XS GIS Cut Line= 2
2162625.47230632447318.8320276742162456.59141488 447517.97749297
#Sta/Elev= 30
       0 3809.59     8.3 3807.21    14.4 3805.14    25.3 3802.12    28.1  3801.6
    34.5 3800.86    55.5 3797.01    62.2 3796.74   107.6 3796.32   113.2 3795.89
   116.1 3795.94   121.8 3796.83   123.7 3796.94   125.7 3796.79     136 3796.82
   144.7 3796.77   155.2  3795.7   187.5 3795.52   192.7 3795.54   195.6 3795.84
   201.2 3796.84   206.9 3797.49   212.6 3797.14   218.5 3797.42   224.6 3798.58
   230.8 3800.15     241 3801.92   243.2 3802.09   249.6 3801.65   261.1 3802.04
#Mann= 4 ,-1,0
       0     .12       0      50      .1       0   125.7    .045       0
     136      .1       0
#XS Ineff= 2 , 0
                           168.2         3801.57
Permanent Ineff=
       F       F
Bank Sta=125.7,136
XS Rating Curve= 0 ,0
Exp/Cntr(USF)=0,0
Exp/Cntr=0.3,0.1

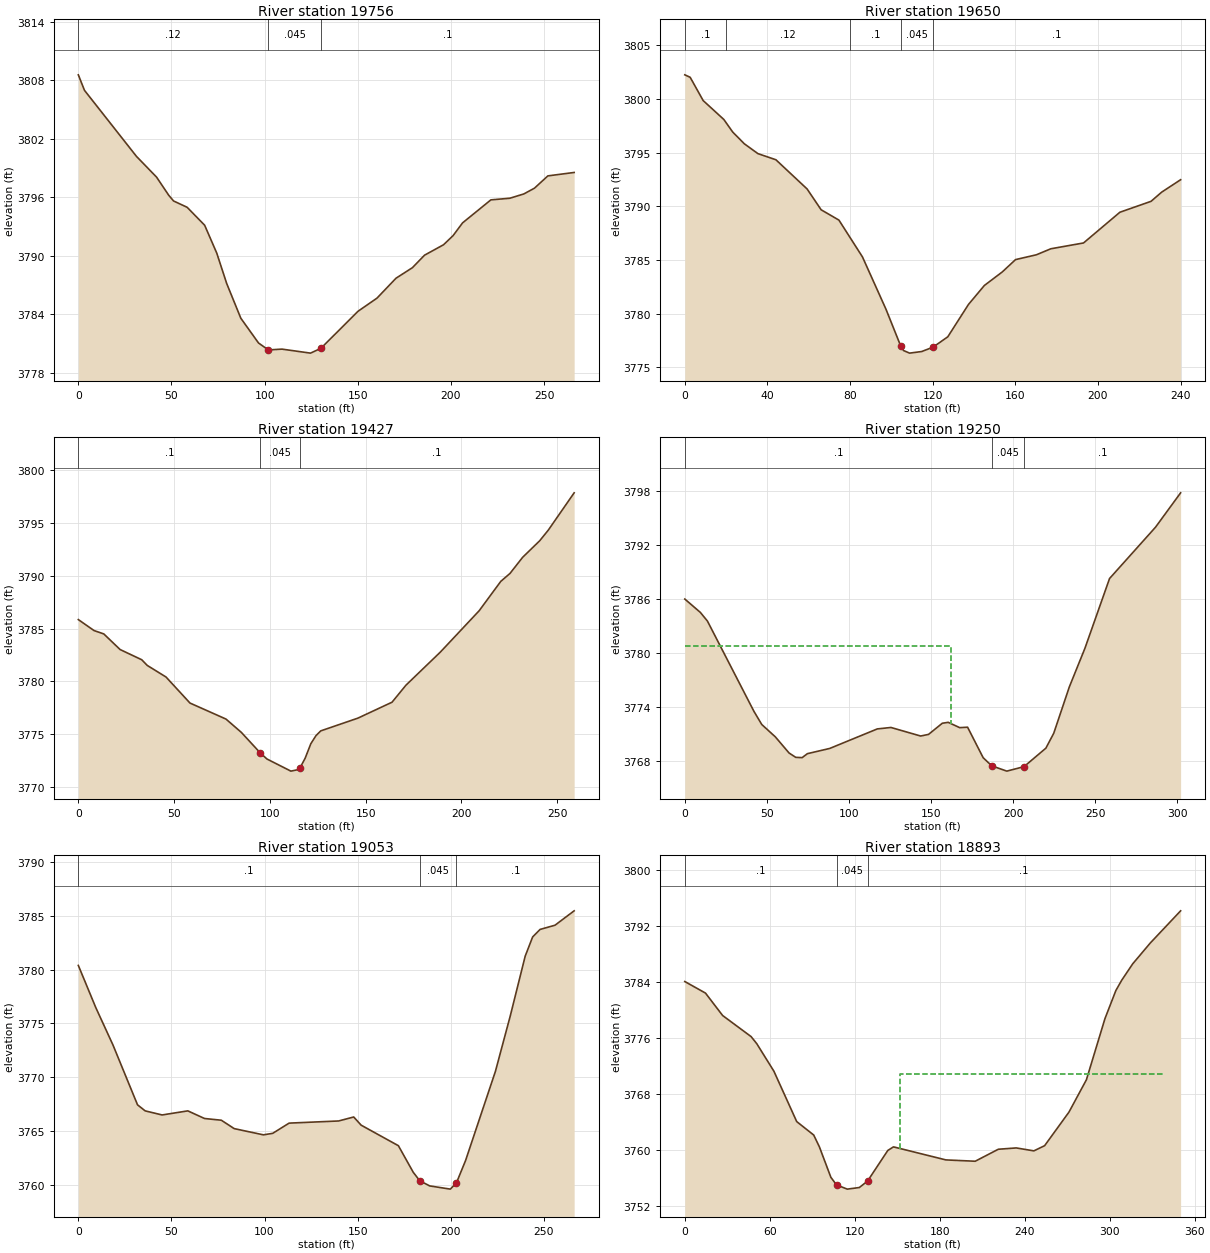
Type RM Length L Ch R = 1 ,19756   ,105.9,106.6,105.9
XS GIS Cut Line= 2
2162546.20235795447259.3810923292162381.26523661447468.257840655
#Sta/Elev= 30
       0 3808.56     3.3 3806.97    31.2  3800.2      42 3798.07    48.5 3796.22
    51.1 3795.63    58.4 3794.98    67.8 3793.14    74.3 3790.28    79.6 3787.18
    87.2 3783.61    96.7 3781.07101.97733780.358   109.3 3780.44   124.6 3780.03
130.16163780.518   150.1 3784.32   160.3 3785.67   170.5 3787.71   179.3 3788.79
   185.8 3790.07     196 3791.14   201.1 3792.07   206.2 3793.38   221.4 3795.74
   231.6 3795.91   239.1 3796.35   244.8 3796.94     252  3798.2   266.1 3798.55
#Mann= 3 ,-1,0
       0     .12       0101.9773    .045       0130.1616      .1       0
Bank Sta=101.9773,130.1616
XS Rating Curve= 0 ,0
Exp/Cntr(USF)=0,0
Exp/Cntr=0.3,0.1

Type RM Length L Ch R = 1 ,19650   ,222.4,222.8,222.7
XS GIS Cut Line= 2
2162461.74997646447194.2091905322162315.52655521447384.499944203
#Sta/Elev= 30
       0 3802.24     2.6 3802.01     8.9 3799.84    18.9 3798.08    23.2 3796.91
    28.8 3795.82    35.4  3794.9    44.1 3794.33    59.2 3791.61      66 3789.67
    74.6 3788.71      86 3785.28    97.4  3780.4   104.6 3776.94   105.9 3776.56
   108.8 3776.32   114.7 3776.47   120.2 3776.88   127.3 3777.84   137.3 3780.85
     145 3782.62   153.6 3783.87   160.1 3785.03   170.2 3785.48   177.2 3786.04
     193 3786.58   210.6 3789.44   225.7 3790.46   230.8 3791.31     240 3792.47
#Mann= 5 ,-1,0
       0      .1       0      20     .12       0      80      .1       0
   104.6    .045       0   120.2      .1       0
Bank Sta=104.6,120.2
XS Rating Curve= 0 ,0
Exp/Cntr(USF)=0,0
Exp/Cntr=0.3,0.1

Type RM Length L Ch R = 1 ,19427   ,178.5,177,175.3
XS GIS Cut Line= 2
2162301.38522112447047.6979354322162136.13272451447247.002461646
#Sta/Elev= 30
       0 3785.85     8.2 3784.81    13.3 3784.49    21.8 3783.01    33.1 3782.04
      36  3781.5    45.8  3780.4    58.3 3777.93    77.1 3776.41    85.1 3775.15
      95  3773.2    98.5 3772.62     111 3771.47   114.7 3771.61   115.83771.799
   118.4 3772.68   121.4 3774.07   124.1 3774.84   126.6 3775.29     146  3776.5
   163.8 3778.01   171.1 3779.63     189 3782.76   209.3 3786.69   220.6 3789.48
   225.4 3790.23     232 3791.76   240.9 3793.33   245.4 3794.34   258.9 3797.88
#Mann= 3 ,-1,0
       0      .1       0      95    .045       0   115.8      .1       0
Bank Sta=95,115.8
XS Rating Curve= 0 ,0
Exp/Cntr(USF)=0,0
Exp/Cntr=0.3,0.1

Type RM Length L Ch R = 1 ,19250   ,176.9,196.6,208.5
XS GIS Cut Line= 3
2162269.45616222446930.8067262392162132.24651352446967.863346691
2162045.11337894447102.068404543
#Sta/Elev= 30
       0 3785.98     9.5 3784.49    13.8 3783.53    42.1 3773.51    46.9 3772.04
    55.2 3770.66    63.5 3768.88    67.6 3768.39    71.5 3768.36    74.7  3768.8
    88.3 3769.38   117.3 3771.55   125.6 3771.71   143.7 3770.76   148.5 3770.94
   156.9 3772.18   160.5 3772.28   167.5 3771.69   172.3 3771.74   181.8 3768.35
     187 3767.45   196.2 3766.86   206.7 3767.36     220 3769.41   224.8 3771.07
   234.3 3776.22   243.8 3780.51   258.8 3788.26   286.8 3793.96   302.1 3797.78
#Mann= 3 ,-1,0
       0      .1       0     187    .045       0   206.7      .1       0
#XS Ineff= 2 , 0
          162.04 3780.79
Permanent Ineff=
       F       F
Bank Sta=187,206.7
XS Rating Curve= 0 ,0
Exp/Cntr(USF)=0,0
Exp/Cntr=0.3,0.1

Type RM Length L Ch R = 1 ,19053   ,156.9,160.2,160.1
XS GIS Cut Line= 3
 2162196.3444516446804.6139106462162073.15622685446868.711848725
2161945.96188098446861.701136748
#Sta/Elev= 30
       0 3780.39     9.4 3776.46    18.6 3772.99    31.8 3767.42    35.9 3766.86
      45 3766.48    58.8 3766.86    67.8 3766.15    76.8 3765.99    83.7 3765.21
    99.4 3764.63   104.4 3764.77   113.2 3765.72   139.8 3765.92   147.9 3766.29
   151.9 3765.53   171.9 3763.62   179.9 3761.14   183.43760.358   188.7 3759.88
   199.8 3759.58   203.1 3760.17     208 3762.25     224 3770.53     232  3775.7
     240 3781.25     244 3783.04     248 3783.74     256 3784.13   266.3 3785.47
#Mann= 3 ,-1,0
       0      .1       0   183.4    .045       0   203.1      .1       0
Bank Sta=183.4,203.1
XS Rating Curve= 0 ,0
Exp/Cntr(USF)=0,0
Exp/Cntr=0.3,0.1

Type RM Length L Ch R = 1 ,18893   ,130.1,124,116.2
XS GIS Cut Line= 3
2162182.71497812446728.603982199 2162028.6214283 446712.60077858
2161839.92543969446762.183282455
#Sta/Elev= 30
       0 3784.02    14.6 3782.37    26.7 3779.17    46.8 3776.16    50.8 3775.15
    62.9 3771.22      79 3764.03      91 3762.11      95 3760.43   103.1 3756.08
   107.1 3754.99   114.7 3754.39   123.2 3754.62     1293755.535   143.3 3759.91
   147.3 3760.42   184.3 3758.56     205 3758.37   221.3 3760.08     234 3760.27
   246.4 3759.85     254 3760.59   271.2 3765.39   283.5    3770   296.6 3778.73
   304.3 3782.74   308.4  3784.2   316.2 3786.55   328.6 3789.52     350 3794.11
#Mann= 3 ,-1,0
       0      .1       0   107.1    .045       0     129      .1       0
#XS Ineff= 1 ,-1
  151.98     339 3770.78
Permanent Ineff=
       F
Bank Sta=107.1,129
XS Rating Curve= 0 ,0
Exp/Cntr(USF)=0,0
Exp/Cntr=0.3,0.1

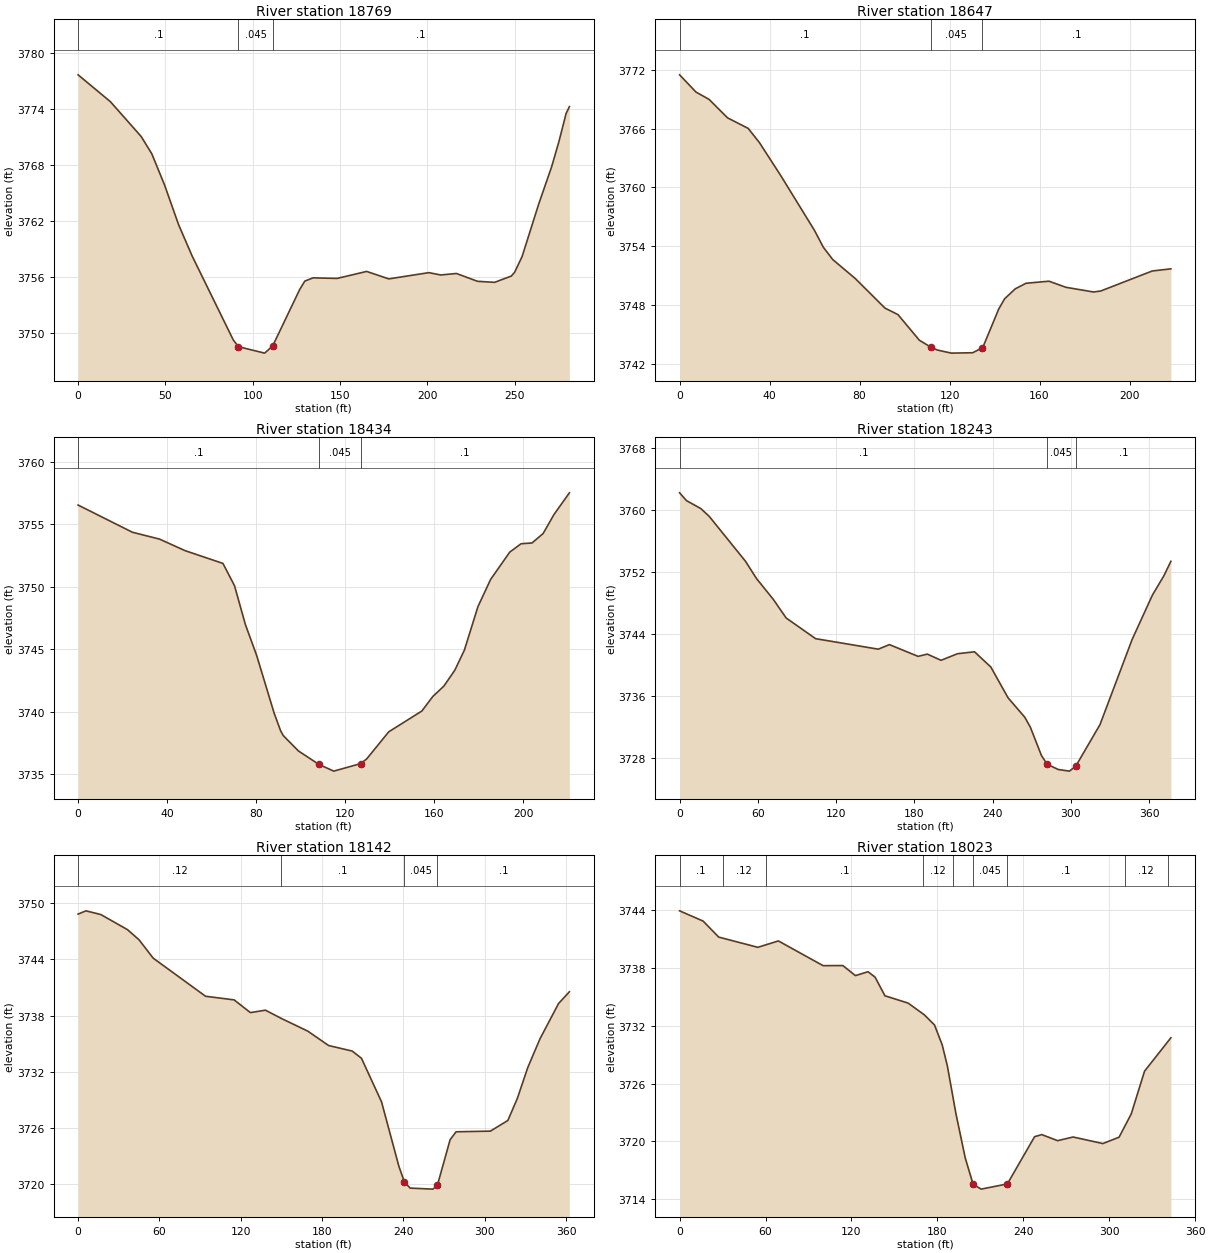
Type RM Length L Ch R = 1 ,18769   ,123.1,122.4,122.6
XS GIS Cut Line= 3
2162104.77378723446556.4795458712161977.30213297 446629.82915698
2161850.54261086446673.981350076
#Sta/Elev= 30
       0  3777.7    18.5 3774.82    36.1 3771.09    42.2 3769.23    49.5 3765.89
    57.5 3761.65    65.3 3758.27    88.8 3749.29    91.8 3748.55   106.8 3747.86
   111.4 3748.63   126.9 3754.69   129.8 3755.58   134.5 3755.93   148.3 3755.87
   165.2 3756.62   177.9 3755.82   200.8 3756.49   207.6 3756.24   216.6  3756.4
   228.7 3755.56   238.5 3755.45     248 3756.12   249.9 3756.52   254.2 3758.21
   263.7 3763.83   271.1 3767.83   275.3 3770.54   279.4 3773.55   281.3 3774.29
#Mann= 3 ,-1,0
       0      .1       0    91.8    .045       0   111.4      .1       0
Bank Sta=91.8,111.4
XS Rating Curve= 0 ,0
Exp/Cntr(USF)=0,0
Exp/Cntr=0.3,0.1

Type RM Length L Ch R = 1 ,18647   ,213,212.8,210.9
XS GIS Cut Line= 2
2162046.11490922446445.0645392352161861.83333725446562.243582286
#Sta/Elev= 30
       0 3771.47     7.3 3769.71    13.1 3768.97    21.3 3767.09    30.5 3766.01
    35.5 3764.56      45 3761.19    59.9 3755.64    63.9  3753.9    68.1 3752.64
    78.1 3750.71    91.3  3747.7    97.1 3747.03   106.6 3744.42   111.6 3743.73
   114.5 3743.43   120.8 3743.11   130.3 3743.15   134.4 3743.63     135 3743.81
   141.9 3747.62   144.5 3748.65   149.2 3749.66     154 3750.23   164.2 3750.44
   171.7 3749.82     184 3749.34   187.2 3749.44   210.1 3751.48   218.4  3751.7
#Mann= 3 ,-1,0
       0      .1       0   111.6    .045       0   134.4      .1       0
Bank Sta=111.6,134.4
XS Rating Curve= 0 ,0
Exp/Cntr(USF)=0,0
Exp/Cntr=0.3,0.1

Type RM Length L Ch R = 1 ,18434   ,185,191.1,193.6
XS GIS Cut Line= 2
2161920.92362391446266.7921489532161742.65123363446396.991085676
#Sta/Elev= 30
       0 3756.55    24.4 3754.37    36.6 3753.82      48  3752.9    65.1 3751.87
    70.3 3750.08    75.2 3746.96    80.2 3744.52    88.1 3739.87      91 3738.46
    92.2 3738.07      99 3736.84   108.2 3735.76   114.9 3735.22     1273735.824
   129.7  3736.2   139.6 3738.37   154.5 3740.04   159.4  3741.2   164.4 3742.04
   169.3 3743.31   173.6 3744.92   179.7 3748.41   185.4 3750.59     194 3752.78
   199.1 3753.45     204 3753.51     209 3754.27   213.9  3755.8   220.8 3757.53
#Mann= 3 ,-1,0
       0      .1       0   108.2    .045       0     127      .1       0
Bank Sta=108.2,127
XS Rating Curve= 0 ,0
Exp/Cntr(USF)=0,0
Exp/Cntr=0.3,0.1

Type RM Length L Ch R = 1 ,18243   ,100.5,100.9,101.5
XS GIS Cut Line= 3
2161923.92821476446021.4172297452161763.68336956446175.652893248
2161619.46300889446230.737058784
#Sta/Elev= 30
       0 3762.25     5.3 3761.24    16.3 3760.21    22.7 3759.21    50.6 3753.38
    59.1 3751.13    71.8 3748.48    81.7 3746.06   104.3 3743.38   152.4 3742.02
   160.9 3742.61   182.9 3741.09     190 3741.38   200.5 3740.58   213.1 3741.43
   226.2 3741.68   238.7 3739.71   251.9 3735.73   264.7 3733.22     269 3731.93
   277.5 3728.27   281.8 3727.14   290.4 3726.45     299 3726.24   303.8 3726.87
   322.4 3732.25   347.1 3743.29   362.6 3749.01   371.3 3751.48   376.8 3753.39
#Mann= 3 ,-1,0
       0      .1       0   281.8    .045       0   303.8      .1       0
Bank Sta=281.8,303.8
XS Rating Curve= 0 ,0
Exp/Cntr(USF)=0,0
Exp/Cntr=0.3,0.1

Type RM Length L Ch R = 1 ,18142   ,126.4,118.5,113.2
XS GIS Cut Line= 4
2161868.34591453445941.909503272 2161712.3889744446090.032989784
2161616.96326674446122.7910685332161579.22026297446149.852090107
#Sta/Elev= 30
       0 3748.84     5.8 3749.19    16.8 3748.79    36.4 3747.18    44.9  3746.1
    55.4 3744.13      94 3740.06   115.1 3739.67   127.1 3738.31   138.2 3738.57
     150 3737.68   169.4 3736.33   184.8 3734.79   202.2  3734.2     209 3733.43
   223.8 3728.78   236.6 3721.89   240.7  3720.2   244.9 3719.55   261.7 3719.44
     265 3719.84   274.4 3724.72   278.8 3725.57   304.1 3725.64     317 3726.78
     324 3729.14   331.7 3732.44   340.7 3735.51   354.4 3739.28   362.4 3740.54
#Mann= 4 ,-1,0
       0     .12       0     150      .1       0   240.7    .045       0
     265      .1       0
Bank Sta=240.7,265
XS Rating Curve= 0 ,0
Exp/Cntr(USF)=0,0
Exp/Cntr=0.3,0.1

Type RM Length L Ch R = 1 ,18023   ,224,213.7,208.3
XS GIS Cut Line= 3
2161777.70479352445841.1417788992161661.52728075445966.333064209
2161533.33140459446081.509046694
#Sta/Elev= 30
       0 3743.89    16.4 3742.83    27.3 3741.17    54.6 3740.11      69 3740.77
   100.2 3738.21     114 3738.22   122.8 3737.18   131.6 3737.58   136.5 3737.02
   143.4 3735.09   159.6 3734.33   170.8 3733.13     178 3732.07   183.4    3730
     187 3727.82     193 3722.86   199.5 3718.28     205 3715.55   210.6 3715.06
   228.9  3715.6   247.9 3720.49   252.9 3720.71     264 3720.08   274.8 3720.46
   295.6 3719.78   306.9 3720.44   315.4 3722.85   324.7 3727.28   343.1 3730.74
#Mann= 9 ,-1,0
       0      .1       0      30     .12       0      60      .1       0
     170     .12       0  190.79      .1       0     205    .045       0
   228.9      .1       0  310.79     .12       0  340.79      .1       0
Bank Sta=205,228.9
XS Rating Curve= 0 ,0
Exp/Cntr(USF)=0,0
Exp/Cntr=0.3,0.1