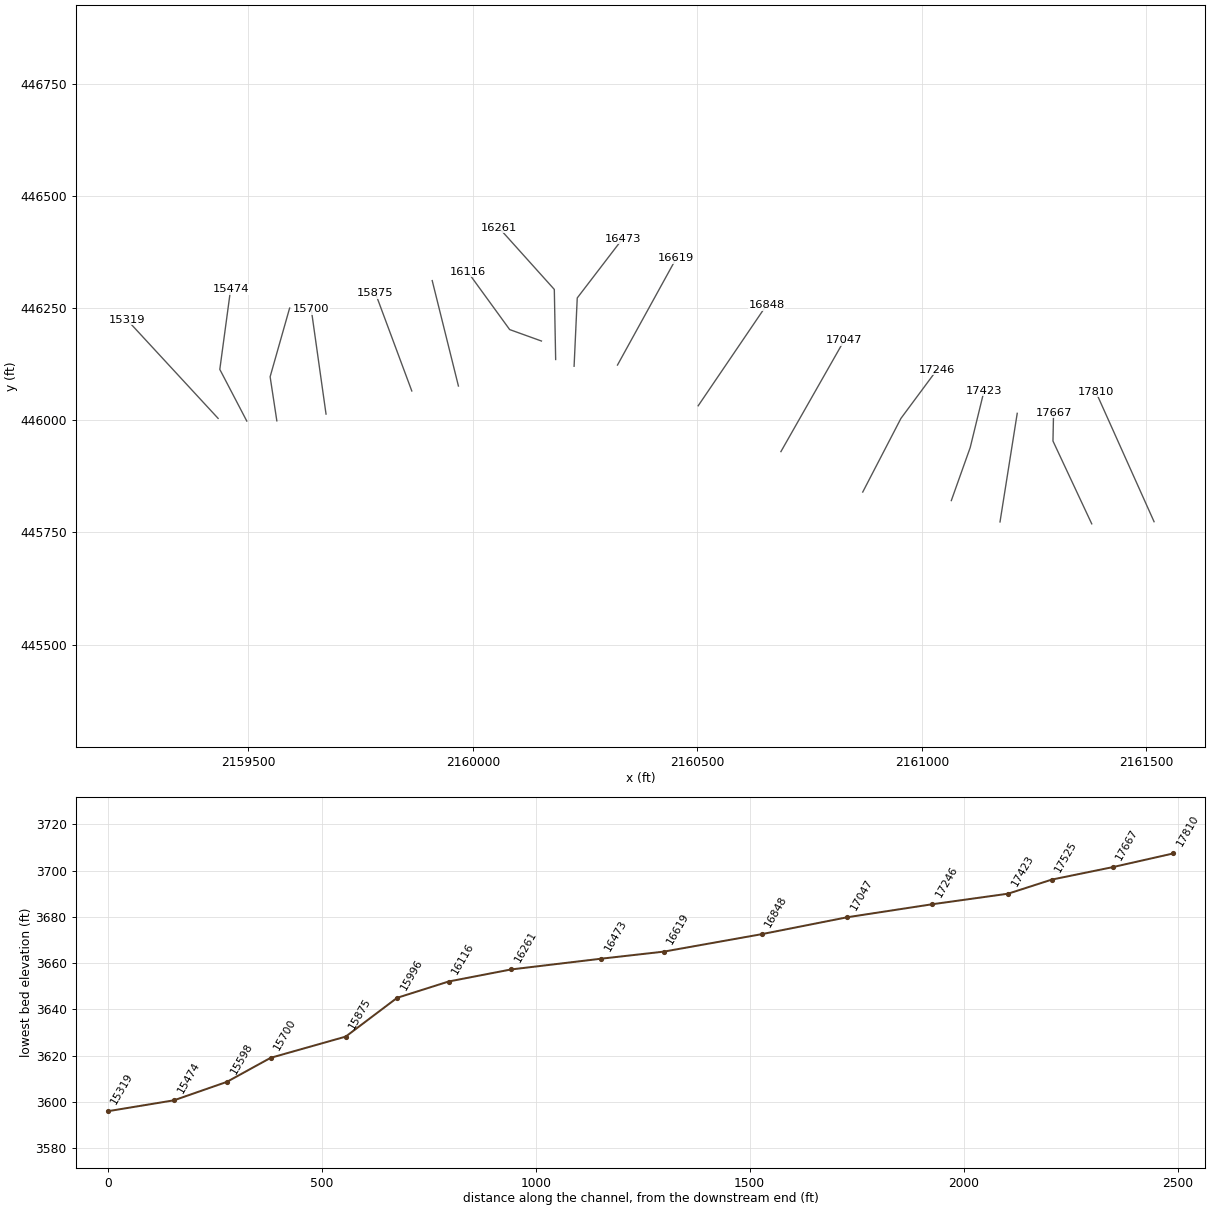
HEC-RAS study DOGWAYFK.prj: DOGWAYFK

--- DOGWAYFK.g01 (geometry) --- (continued)

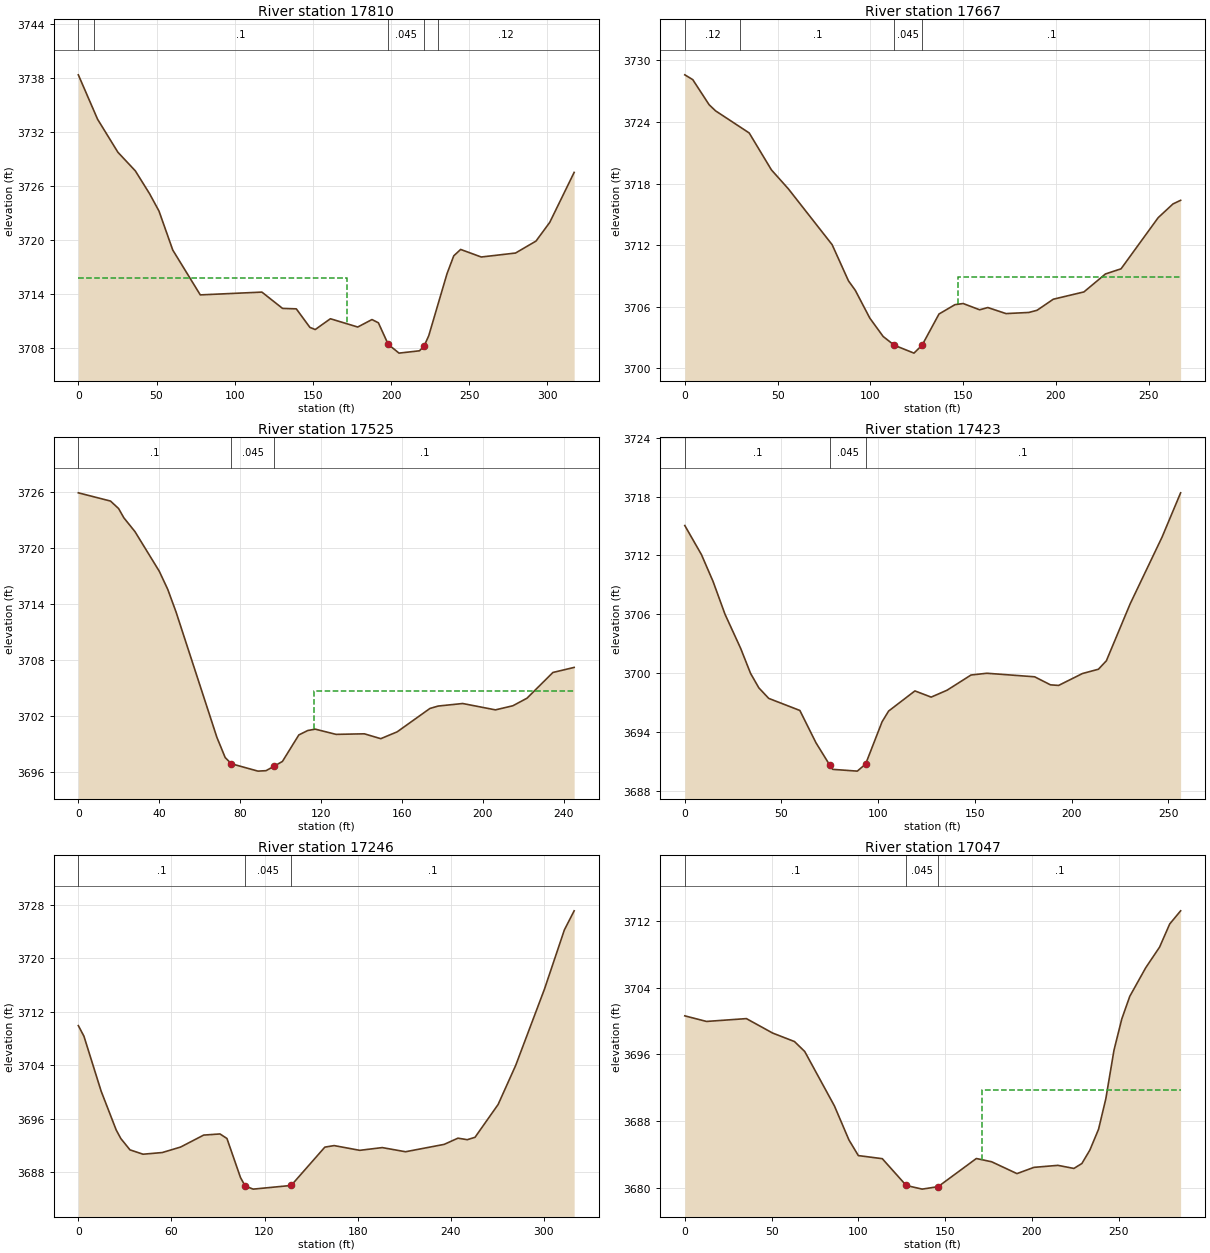
Type RM Length L Ch R = 1 ,17810   ,140.3,142.4,143.9
XS GIS Cut Line= 2
2161517.26960763445774.0486520262161387.53853504446063.448737037
#Sta/Elev= 30
       0 3738.36    12.3 3733.43    25.3 3729.76    36.5 3727.68    45.6 3725.14
    51.6 3723.22    60.4 3718.89      78 3713.91   117.4 3714.22   130.6 3712.41
   139.4 3712.36   148.1  3710.3   151.5 3710.06   161.2 3711.26   178.7 3710.34
   187.8 3711.17   191.9 3710.81   198.2 3708.41   205.1 3707.44   218.2  3707.7
   221.1 3708.22   224.1 3709.37   235.8 3716.27   240.1 3718.25   244.5 3718.96
   257.7 3718.12   279.6 3718.56   292.7 3719.89   301.5 3721.97   317.1 3727.52
#Mann= 5 ,-1,0
       0     .06       0      10      .1       0   198.2    .045       0
   221.1      .1       0     230     .12       0
#XS Ineff= 2 , 0
          171.51 3715.83
Permanent Ineff=
       F       F
Bank Sta=198.2,221.1
XS Rating Curve= 0 ,0
Exp/Cntr(USF)=0,0
Exp/Cntr=0.3,0.1

Type RM Length L Ch R = 1 ,17667   ,150.7,142.1,136.1
XS GIS Cut Line= 3
2161378.40442821445769.2748444882161292.06343168445953.855595748
2161293.37642088446017.240846168
#Sta/Elev= 30
       0 3728.59     4.3 3728.12    13.1 3725.68    16.6 3725.08    34.7 3722.93
    46.7 3719.33    55.8 3717.49    79.4 3712.05    88.2 3708.53    91.9  3707.6
    99.7  3704.9   106.9 3703.11   112.9 3702.26   123.5 3701.49   127.9 3702.27
     137  3705.3   145.6 3706.21     150 3706.32   158.9 3705.71   163.3 3705.93
   173.1 3705.34   185.4 3705.45   189.8 3705.66   198.6 3706.74   215.1 3707.45
   226.7  3709.2   235.1  3709.7   255.1 3714.68   263.1 3716.02   267.2 3716.37
#Mann= 4 ,-1,0
       0     .12       0      30      .1       0   112.9    .045       0
   127.9      .1       0
#XS Ineff= 2 , 0
                          147.47         3708.95
Permanent Ineff=
       F       F
Bank Sta=112.9,127.9
XS Rating Curve= 0 ,0
Exp/Cntr(USF)=0,0
Exp/Cntr=0.3,0.1

Type RM Length L Ch R = 1 ,17525   ,106.5,101.9,100.7
XS GIS Cut Line= 2
2161174.08204206445773.5132726342161212.44381775 446015.60162162
#Sta/Elev= 30
       0 3725.87    15.9 3724.99    19.9 3724.19    22.5  3723.2      28 3721.72
      40 3717.49    44.2 3715.55    48.3 3713.13    68.5 3699.72    72.6 3697.56
75.634113696.899    88.8 3696.11    92.8 3696.16    96.9 3696.65   100.9 3697.15
     109 3699.98   113.4 3700.45   117.1  3700.6   127.4 3700.04   141.4  3700.1
   149.5 3699.58   157.6 3700.31   173.8 3702.81   177.9 3703.07     190 3703.34
   206.2 3702.66   214.8  3703.1   221.8 3703.91   234.6 3706.66   245.1  3707.2
#Mann= 3 ,-1,0
       0      .1       075.63411    .045       0    96.9      .1       0
#XS Ineff= 2 , 0
                          116.74         3704.67
Permanent Ineff=
       F       F
Bank Sta=75.63411,96.9
XS Rating Curve= 0 ,0
Exp/Cntr(USF)=0,0
Exp/Cntr=0.3,0.1

Type RM Length L Ch R = 1 ,17423   ,180.3,176.8,173.5
XS GIS Cut Line= 3
2161065.61676268445821.1111732492161107.68103454445939.291746582
 2161138.7284733446066.486092457
#Sta/Elev= 30
       0 3715.05     8.6 3712.09    14.6 3709.36    20.8 3706.01    28.9 3702.53
      34 3699.99    38.3 3698.51    43.4 3697.44    59.5 3696.21    67.8 3692.93
      75 3690.63    76.5 3690.21    89.2 3690.03    93.5 3690.75     102 3695.05
   105.4 3696.15     119  3698.2   127.4 3697.57   135.6 3698.27     148 3699.82
   156.2    3700   180.9 3699.64   189.1 3698.82   193.3 3698.76   205.6 3699.97
   213.9 3700.41     218 3701.27   230.3 3707.07   246.8 3713.87   256.4 3718.38
#Mann= 3 ,-1,0
       0      .1       0      75    .045       0    93.5      .1       0
Bank Sta=75,93.5
XS Rating Curve= 0 ,0
Exp/Cntr(USF)=0,0
Exp/Cntr=0.3,0.1

Type RM Length L Ch R = 1 ,17246   ,200,199.3,198.1
XS GIS Cut Line= 3
2160868.31529703445840.1402486162160953.44537104446004.391214943
2161033.56779364446112.556485451
#Sta/Elev= 30
       0 3709.93     3.6 3708.35    14.7 3700.13    24.4 3694.33    27.4 3693.04
    33.3 3691.35    41.7  3690.7    54.1 3690.95    65.9 3691.77    80.8 3693.56
    91.3 3693.73    95.8 3693.05   104.5 3687.23   107.5 3685.95   112.7 3685.48
   137.2 3686.03   158.9 3691.76   164.9 3691.99   181.4 3691.28   195.9 3691.69
   210.9 3691.07   235.8 3692.17   244.7  3693.1   250.7 3692.87   255.7 3693.23
   270.6 3698.14   281.9 3703.97   300.5 3715.41   313.3 3724.24   319.6 3727.09
#Mann= 3 ,-1,0
       0      .1       0   107.5    .045       0   137.2      .1       0
Bank Sta=107.5,137.2
XS Rating Curve= 0 ,0
Exp/Cntr(USF)=0,0
Exp/Cntr=0.3,0.1

Type RM Length L Ch R = 1 ,17047   ,200.7,199.6,198.4
XS GIS Cut Line= 2
2160686.03678562 445930.277974042160827.25255545446178.657484095
#Sta/Elev= 30
       0 3700.61    12.5 3699.94    35.5 3700.28    50.6 3698.55    63.2 3697.53
    69.1 3696.34    86.2 3689.82    94.6 3685.73     100 3683.86   113.8 3683.49
   127.6 3680.28   136.8 3679.84     146 3680.14     168 3683.51   176.8 3683.12
   191.4  3681.7   201.2 3682.45     215 3682.69   224.2 3682.32   228.8 3682.91
   233.4 3684.52   238.4 3687.01   242.6 3690.67   247.3 3696.49   251.8 3700.24
   256.4 3702.95   265.6 3706.38   273.6 3708.86   279.4 3711.62   285.7  3713.2
#Mann= 3 ,-1,0
       0      .1       0   127.6    .045       0     146      .1       0
#XS Ineff= 2 , 0
                          171.03         3691.69
Permanent Ineff=
       F       F
Bank Sta=127.6,146
XS Rating Curve= 0 ,0
Exp/Cntr(USF)=0,0
Exp/Cntr=0.3,0.1

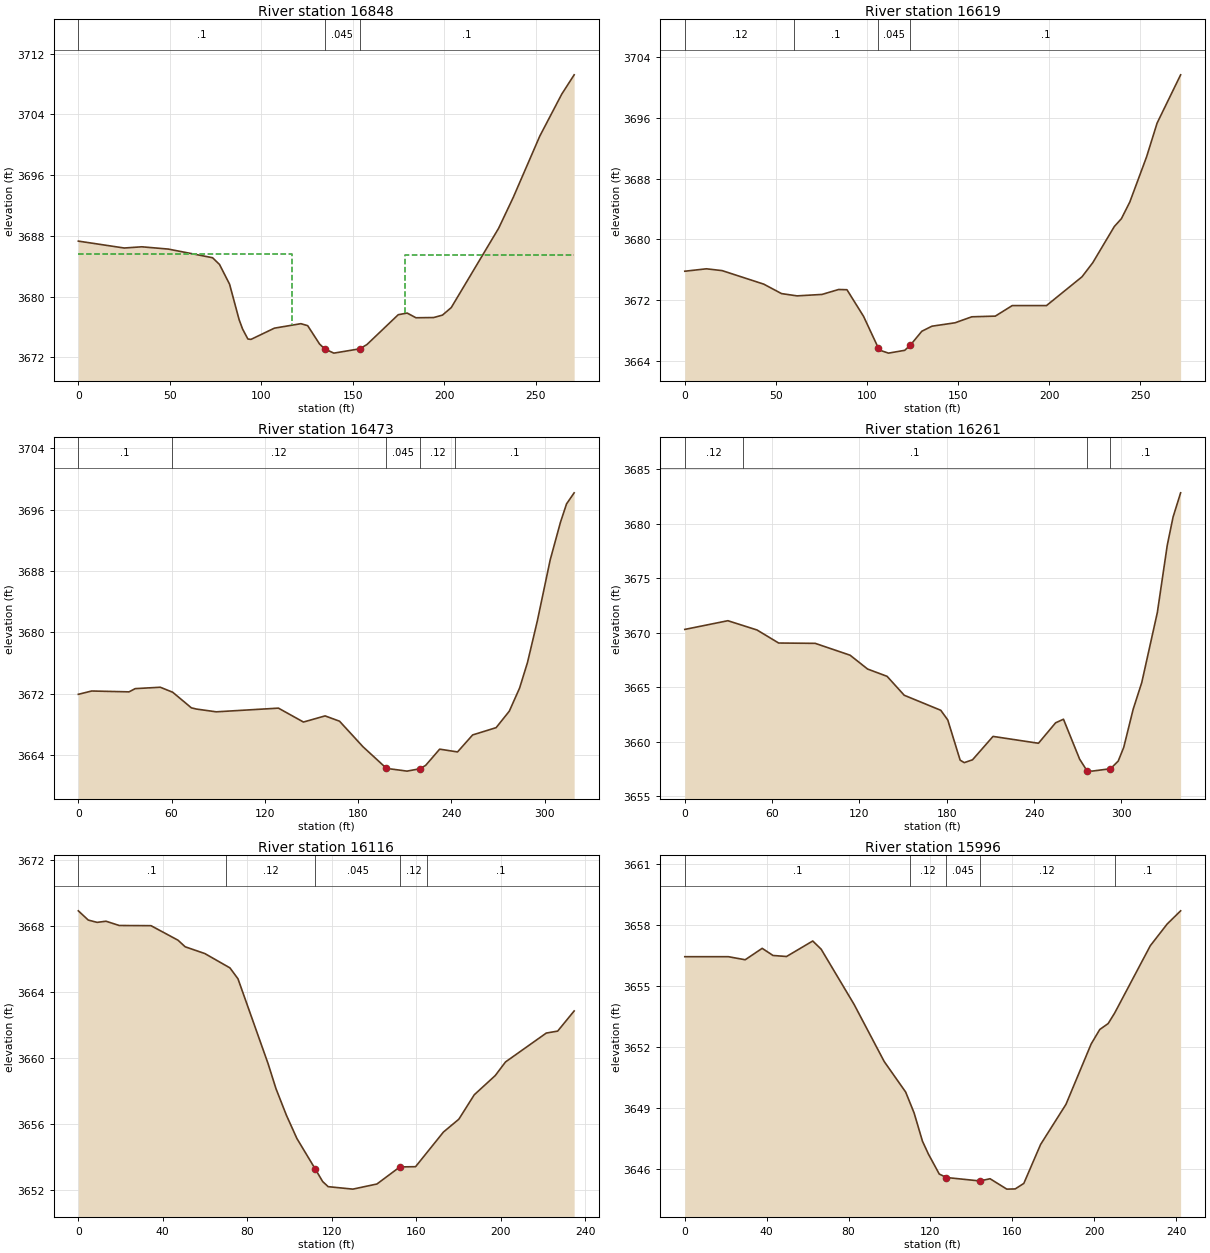
Type RM Length L Ch R = 1 ,16848   ,228.5,229,231.2
XS GIS Cut Line= 2
2160501.75521364446032.4340628532160653.98781658446256.776846129
#Sta/Elev= 30
       0  3687.3    25.1 3686.39    34.7 3686.55    49.2 3686.25    73.4 3685.11
    77.2 3684.22    82.7 3681.62    87.9 3676.96    89.8 3675.72    92.7  3674.4
    94.4 3674.35   107.2 3675.83   121.7 3676.42   125.4 3676.16   131.9 3673.74
   134.7  3673.1   139.7 3672.54   153.9 3673.11   157.8 3673.67   174.9  3677.6
   179.8 3677.82   184.6  3677.2   194.3 3677.23   199.1 3677.55   203.9 3678.54
   229.8 3688.99   237.8 3693.06   252.3 3701.13   264.3 3706.66   271.1 3709.21
#Mann= 3 ,-1,0
       0      .1       0   134.7    .045       0   153.9      .1       0
#XS Ineff= 2 , 0
          116.59 3685.54  178.79          3685.5
Permanent Ineff=
       F       F
Bank Sta=134.7,153.9
XS Rating Curve= 0 ,0
Exp/Cntr(USF)=0,0
Exp/Cntr=0.3,0.1

Type RM Length L Ch R = 1 ,16619   ,148.4,145.7,144.8
XS GIS Cut Line= 2
2160321.98954595446123.2374711272160453.19001295446361.601678357
#Sta/Elev= 30
       0 3675.79    11.9 3676.11    20.5 3675.87    43.3 3674.09    53.1 3672.84
    61.6 3672.54    75.3 3672.73    84.4 3673.38      89 3673.35    98.1 3669.84
   106.1 3665.72   107.2 3665.36   111.8 3664.99   120.7 3665.36   123.8 3666.05
   130.1 3667.88   135.6 3668.54   148.3 3668.99   157.5 3669.78   170.4 3669.87
   179.7 3671.26   198.5 3671.26     218 3675.06   223.9 3676.92   235.7 3681.68
   239.6 3682.72   244.2 3684.91   253.4 3690.86   259.2 3695.33   272.1 3701.69
#Mann= 4 ,-1,0
       0     .12       0      60      .1       0   106.1    .045       0
   123.8      .1       0
Bank Sta=106.1,123.8
XS Rating Curve= 0 ,0
Exp/Cntr(USF)=0,0
Exp/Cntr=0.3,0.1

Type RM Length L Ch R = 1 ,16473   ,197.6,211.4,234.3
XS GIS Cut Line= 3
2160225.33285567446120.5687277112160232.34356765446272.801330648
2160333.49812618446405.003327936
#Sta/Elev= 30
       0 3671.95     8.6 3672.38    32.6 3672.27    36.6 3672.69    52.7 3672.87
    60.7 3672.22    72.7 3670.19      76 3670.03    88.7 3669.67   128.7 3670.15
   144.8 3668.34   158.7 3669.14     168 3668.45   183.1 3665.12   198.2 3662.31
   211.4 3661.95   219.7 3662.26   223.4  3662.7   232.4 3664.81   243.9 3664.45
   253.6 3666.66   268.7 3667.61   277.2 3669.76   283.8 3672.76   288.9  3676.1
   295.2 3681.49   303.5 3689.46   310.1 3694.35     314 3696.74   318.9 3698.18
#Mann= 5 ,-1,0
       0      .1       0      60     .12       0   198.2    .045       0
   219.7     .12       0  242.39      .1       0
Bank Sta=198.2,219.7
XS Rating Curve= 0 ,0
Exp/Cntr(USF)=0,0
Exp/Cntr=0.3,0.1

Type RM Length L Ch R = 1 ,16261   ,148.5,145.8,145.6
XS GIS Cut Line= 3
2160184.27011409446135.5916819482160181.26552324446291.830406016
 2160058.0772985446429.040054716
#Sta/Elev= 30
       0  3670.3    29.6  3671.1    49.6 3670.25    64.5 3669.05    89.6 3669.02
   113.6 3667.93   125.6 3666.66     139 3665.99   150.8 3664.25   175.9 3662.87
   180.7 3661.98   189.2 3658.29     192 3658.06   197.7 3658.32   211.8 3660.47
     243 3659.84   254.8 3661.72   260.2 3662.05   271.3 3658.38   276.3 3657.33
   279.8 3657.28   292.5  3657.5   297.8  3658.2   301.6 3659.46   308.1 3662.97
     314 3665.42   324.7 3671.85   331.5 3678.02   335.5 3680.62   340.7 3682.85
#Mann= 4 ,-1,0
       0     .12       0      40      .1       0   276.3    .045       0
   292.5      .1       0
Bank Sta=276.3,292.5
XS Rating Curve= 0 ,0
Exp/Cntr(USF)=0,0
Exp/Cntr=0.3,0.1

Type RM Length L Ch R = 1 ,16116   ,127.2,120.1,115.3
XS GIS Cut Line= 3
2160152.57988934 446176.812832232160081.81892458446202.326567619
 2159988.0950179446331.436324292
#Sta/Elev= 30
       0 3668.94     4.7 3668.38     8.9 3668.24    13.1 3668.31    19.4 3668.05
    34.4 3668.04    47.2 3667.16    50.6 3666.76    59.9 3666.35    71.8 3665.48
    75.6 3664.82    89.9 3659.66    93.6 3658.16    98.5 3656.56   103.5 3655.14
   112.1 3653.31   115.7 3652.53   118.3 3652.22     130 3652.07   141.4 3652.38
152.26433653.416   159.7 3653.43   172.9 3655.53   180.2 3656.31   187.5 3657.79
   197.4 3658.95   202.3 3659.78   221.6 3661.53     227 3661.65   234.8 3662.87
#Mann= 5 ,-1,0
       0      .1       0      70     .12       0   112.1    .045       0
152.2643     .12       0  165.22      .1       0
Bank Sta=112.1,152.2643
XS Rating Curve= 0 ,0
Exp/Cntr(USF)=0,0
Exp/Cntr=0.3,0.1

Type RM Length L Ch R = 1 ,15996   ,118.4,120.3,122.7
XS GIS Cut Line= 2
2159967.66521499446076.5024789972159909.27037896446311.506087407
#Sta/Elev= 30
       0 3656.43    21.3 3656.43    29.5 3656.28    37.8 3656.84    43.1 3656.49
    49.7 3656.44    62.5  3657.2    66.6  3656.8    82.7 3654.09    97.4 3651.29
   107.9 3649.79     112 3648.77   116.1 3647.38     119 3646.75   124.3 3645.77
   127.8  3645.6   144.2 3645.43   149.1 3645.54   157.3 3645.03   161.4 3645.04
   165.6 3645.31   173.8 3647.22   186.2 3649.19   198.5 3652.15   202.7 3652.86
   206.8 3653.15     210 3653.67   227.4 3656.97   235.6 3658.03   242.2 3658.68
#Mann= 5 ,-1,0
       0      .1       0     110     .12       0   127.8    .045       0
   144.2     .12       0     210      .1       0
Bank Sta=127.8,144.2
XS Rating Curve= 0 ,0
Exp/Cntr(USF)=0,0
Exp/Cntr=0.3,0.1

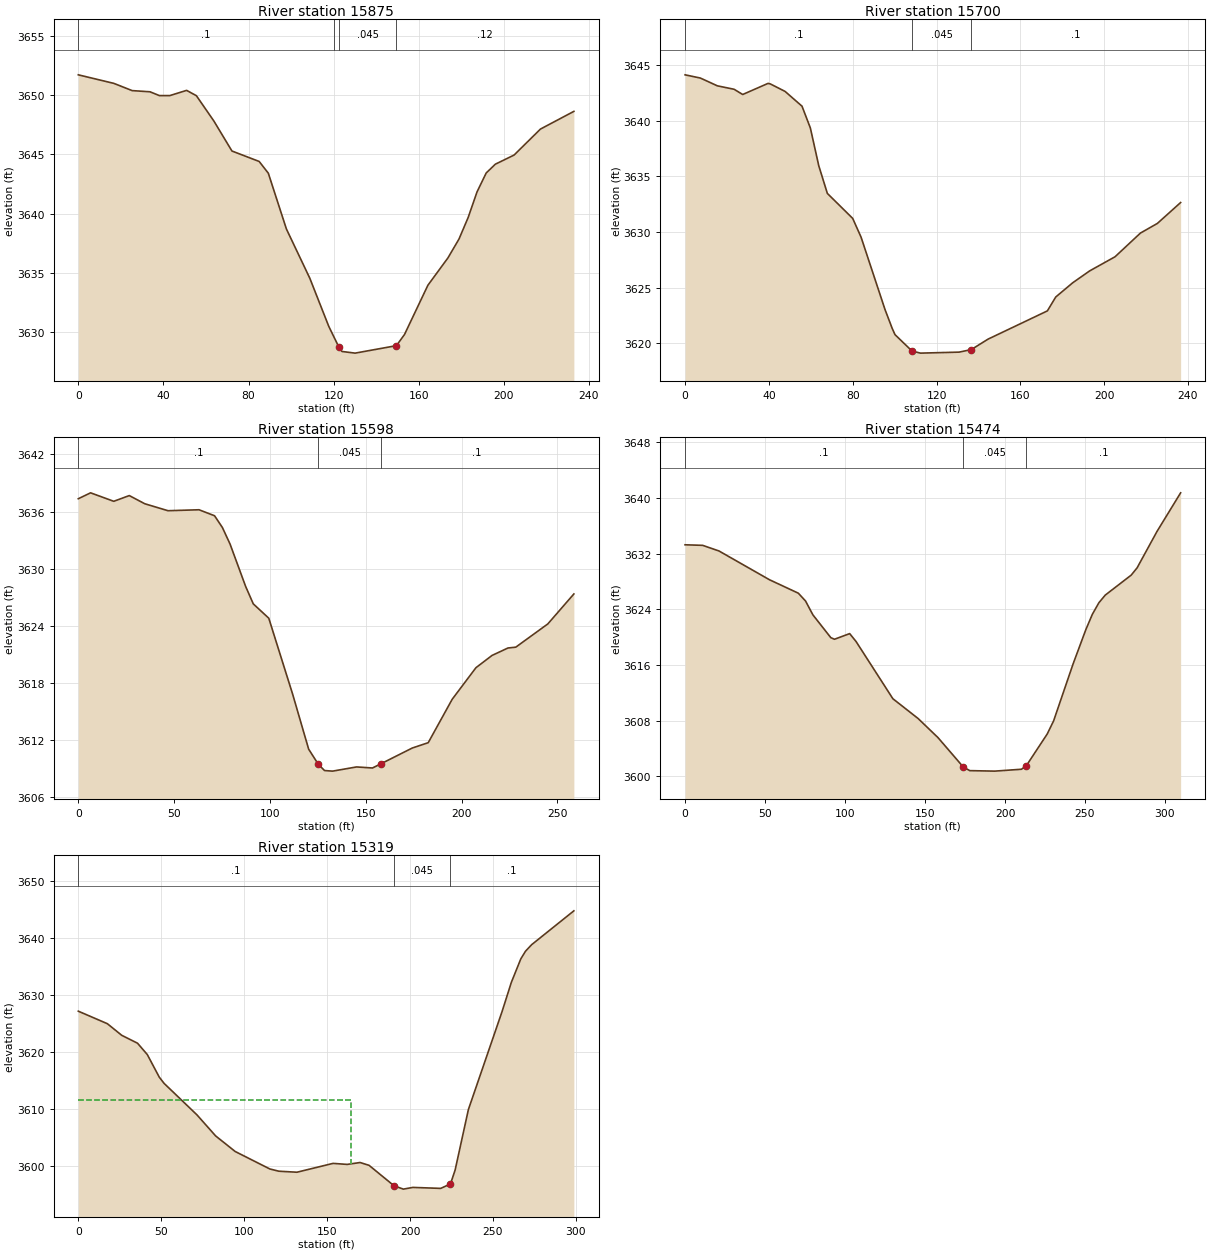
Type RM Length L Ch R = 1 ,15875   ,176.7,175.3,170.8
XS GIS Cut Line= 2
 2159863.7804237446065.4845621752159782.65647082446283.818163756
#Sta/Elev= 30
       0 3651.71    16.7 3650.99    25.3 3650.38    33.7 3650.28    38.1 3649.96
      43 3649.96    50.9  3650.4    55.5 3649.95    63.7 3647.82    72.2 3645.29
      85 3644.41    89.3 3643.42    97.8 3638.72   108.8 3634.57   117.7 3630.52
   122.4 3628.79   123.9  3628.4   130.1 3628.26   149.5 3628.89   153.3 3629.83
   164.3 3633.98   173.7 3636.28   178.9 3637.87   183.2 3639.68   187.4 3641.85
   191.7 3643.44     196 3644.18   204.8 3644.95   217.2 3647.14   232.9 3648.63
#Mann= 4 ,-1,0
       0      .1       0     120     .12       0   122.4    .045       0
   149.5     .12       0
Bank Sta=122.4,149.5
XS Rating Curve= 0 ,0
Exp/Cntr(USF)=0,0
Exp/Cntr=0.3,0.1

Type RM Length L Ch R = 1 ,15700   ,106.5,102.1,97.9
XS GIS Cut Line= 2
2159672.75315596446013.9641192512159639.74133443446248.103520162
#Sta/Elev= 30
       0 3644.14     7.3 3643.85    15.4 3643.15    23.4 3642.84    27.5 3642.37
    39.6 3643.37    40.7 3643.32    47.7 3642.65    55.8 3641.32    59.8 3639.35
    63.8 3635.96    67.9 3633.47      80 3631.22      84 3629.53    95.4 3623.03
    98.9  3621.3   100.2 3620.76   108.3 3619.29   112.3  3619.1   130.8 3619.19
   136.6 3619.42   144.6 3620.36   172.9  3622.9   176.9 3624.15     185 3625.43
   193.1  3626.5   205.2 3627.77   217.3  3629.9   225.4 3630.77   236.5 3632.65
#Mann= 3 ,-1,0
       0      .1       0   108.3    .045       0   136.6      .1       0
Bank Sta=108.3,136.6
XS Rating Curve= 0 ,0
Exp/Cntr(USF)=0,0
Exp/Cntr=0.3,0.1

Type RM Length L Ch R = 1 ,15598   ,119.8,123.8,128.1
XS GIS Cut Line= 3
2159563.17415567445998.8800750072159548.21938059446097.154311251
2159591.65944154446250.262722791
#Sta/Elev= 30
       0 3637.35     6.4 3637.97    18.5 3637.08    26.6 3637.68    34.7 3636.82
    46.8 3636.09      63 3636.19    71.1 3635.56    75.2 3634.32    79.2 3632.58
    87.3 3628.14    91.3  3626.3    99.4 3624.79   111.9 3616.77   120.2 3611.03
   125.3 3609.42   128.5 3608.78   132.7 3608.72   145.2 3609.16   153.5 3609.05
   157.7 3609.47   174.3 3611.15   182.6 3611.71   195.1 3616.27   207.5 3619.59
   215.9 3620.88   224.2 3621.66   228.3 3621.75     245 3624.19   258.6 3627.34
#Mann= 3 ,-1,0
       0      .1       0   125.3    .045       0   157.7      .1       0
Bank Sta=125.3,157.7
XS Rating Curve= 0 ,0
Exp/Cntr(USF)=0,0
Exp/Cntr=0.3,0.1

Type RM Length L Ch R = 1 ,15474   ,139.4,154.7,178.3
XS GIS Cut Line= 3
2159496.21881003445998.3820332482159436.12699308446113.558015734
2159460.16371986446291.830406016
#Sta/Elev= 30
       0 3633.28      11  3633.2    21.2 3632.39    52.8 3628.25    70.8 3626.32
    75.3  3625.2    79.9 3623.21    91.1 3619.93    93.4  3619.7   102.9 3620.51
   106.9 3619.37   129.9 3611.15   145.7  3608.3   158.1 3605.56   173.9 3601.34
     178 3600.81   193.6 3600.74   210.3 3601.01   213.4 3601.54   226.4 3606.08
   230.4 3607.97   242.5 3616.11   250.5 3621.06   254.6 3623.28   258.7 3624.95
   262.7 3626.05   278.9 3628.92   282.6 3629.97     295 3635.19   309.8 3640.75
#Mann= 3 ,-1,0
       0      .1       0   173.9    .045       0   213.4      .1       0
Bank Sta=173.9,213.4
XS Rating Curve= 0 ,0
Exp/Cntr(USF)=0,0
Exp/Cntr=0.3,0.1

Type RM Length L Ch R = 1 ,15319   ,160.3,168.5,184.2
XS GIS Cut Line= 2
2159432.36077238446004.3404968622159229.70394892 446223.88538894
#Sta/Elev= 30
       0 3627.19    17.5    3625    26.2 3622.96    35.7 3621.58    41.6 3619.59
    48.8 3615.64    51.7 3614.55    71.5 3609.04    82.8 3605.34    94.6 3602.61
   115.5 3599.55   120.9 3599.16   131.8 3598.98   153.6 3600.53   162.1 3600.35
   169.9 3600.68   175.3 3600.19   190.4  3596.6     196 3596.02   201.7 3596.32
   218.5 3596.15   224.4 3596.93   227.2 3599.36   235.2 3609.96   255.5 3627.12
   261.1 3632.24   266.8 3636.35   269.6 3637.68   273.3 3638.83   298.8 3644.77
#Mann= 3 ,-1,0
       0      .1       0   190.4    .045       0   224.4      .1       0
#XS Ineff= 2 , 0
          164.52 3611.55
Permanent Ineff=
       F       F
Bank Sta=190.4,224.4
XS Rating Curve= 0 ,0
Exp/Cntr(USF)=0,0
Exp/Cntr=0.3,0.1