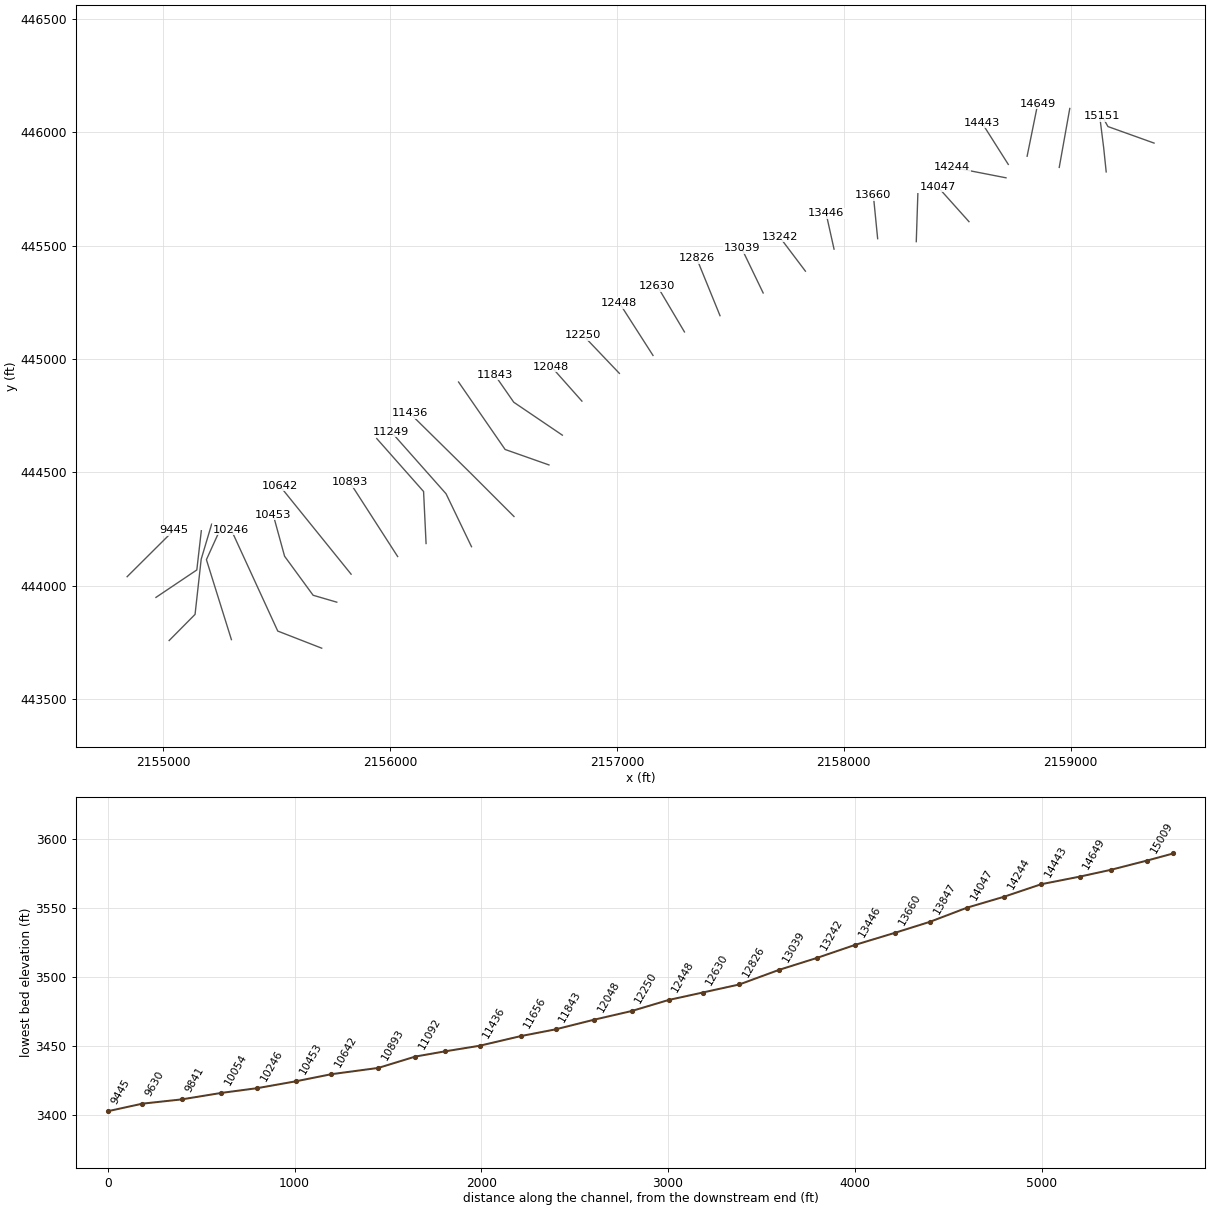
HEC-RAS study DOGWAYFK.prj: DOGWAYFK

--- DOGWAYFK.g01 (geometry) --- (continued)

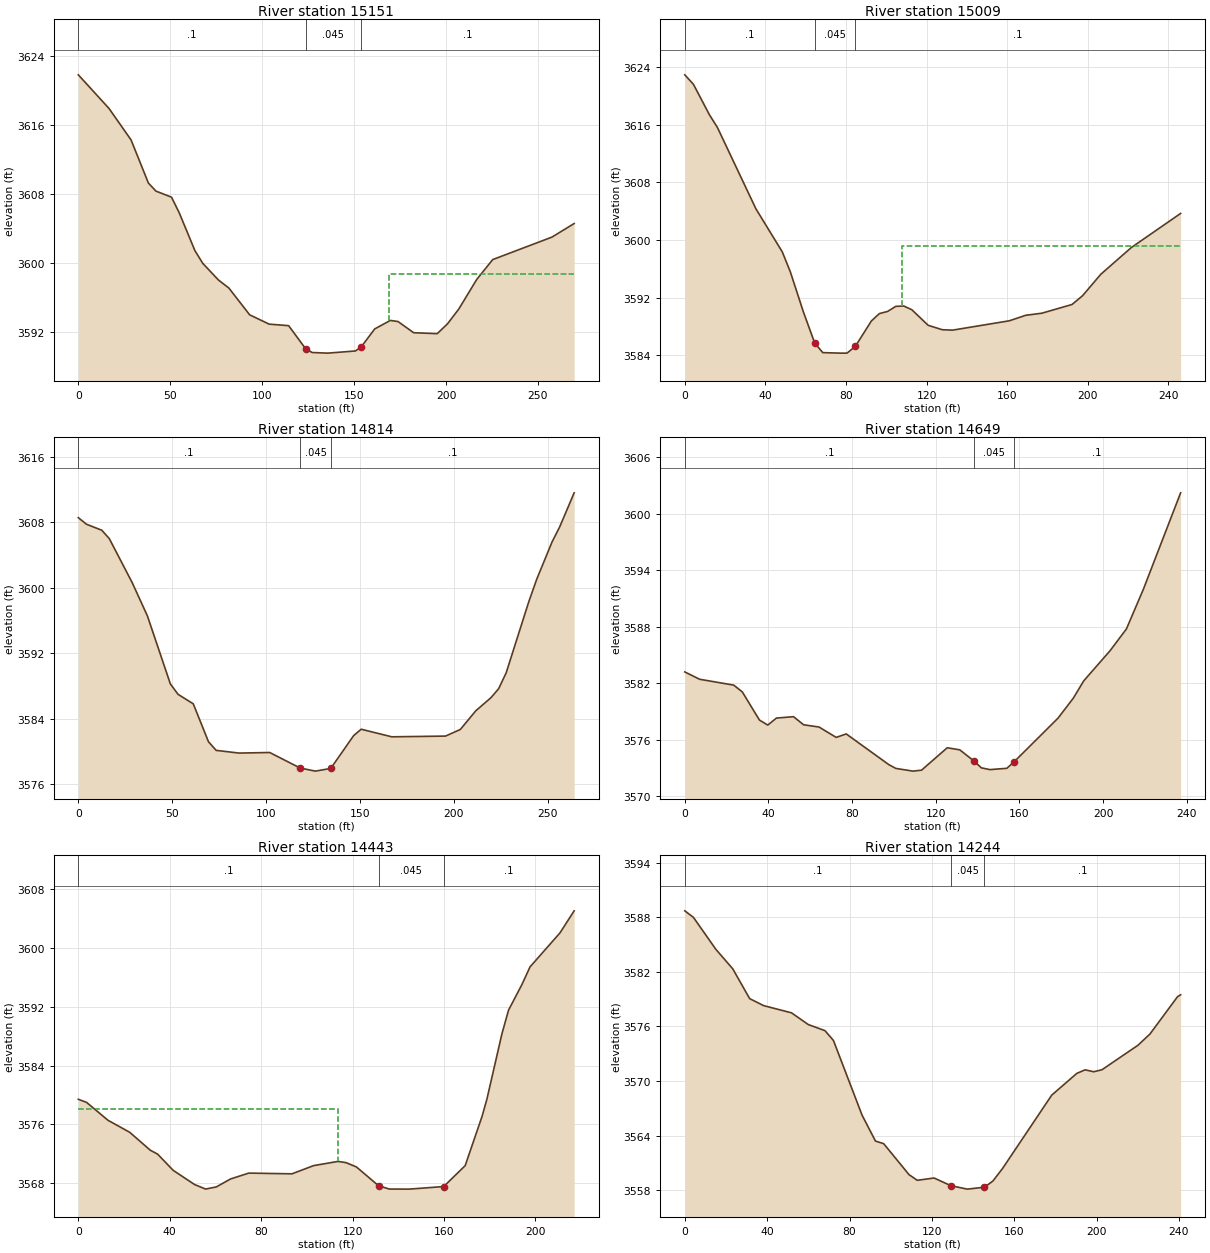
Type RM Length L Ch R = 1 ,15151   ,158.5,141.5,122.1
XS GIS Cut Line= 3
2159367.87905582445952.1410120332159164.45459288446025.066762898
2159138.35485047446071.892771348
#Sta/Elev= 30
       0 3621.83    16.7 3617.92    28.7 3614.26    38.1 3609.26    42.2 3608.32
    50.7 3607.61    54.9 3605.79    63.4 3601.41    67.7 3599.92    76.2 3597.99
    81.9 3597.05    93.2 3593.94   103.8 3592.86   114.4 3592.68   123.6 3590.01
   127.2 3589.56   135.7 3589.49   150.7 3589.74   153.8 3590.19   161.2  3592.3
   169.7 3593.29   173.9 3593.16   182.4 3591.86   195.2 3591.75   200.8 3592.89
     207 3594.63   216.7 3598.05   225.4 3600.36   257.6 3602.97   269.7 3604.55
#Mann= 3 ,-1,0
       0      .1       0   123.6    .045       0   153.8      .1       0
#XS Ineff= 2 , 0
                          169.12         3598.63
Permanent Ineff=
       F       F
Bank Sta=123.6,153.8
XS Rating Curve= 0 ,0
Exp/Cntr(USF)=0,0
Exp/Cntr=0.3,0.1

Type RM Length L Ch R = 1 ,15009   ,198.4,195.3,190.9
XS GIS Cut Line= 3
2159156.79061192445825.0631404482159145.78667141445930.823235377
2159128.29453299446069.452750177
#Sta/Elev= 30
       0 3622.94     4.3 3621.62    12.2 3617.41    16.2 3615.63    35.3 3604.34
    48.4 3598.36    52.4 3595.58    58.9    3590    64.5  3585.7    68.5 3584.38
    77.2 3584.31    80.5 3584.31    84.6 3585.23    92.6 3588.77    96.6  3589.8
   100.7  3590.1   104.7  3590.8   108.7 3590.85   112.7 3590.33   120.8 3588.17
   127.8 3587.56   132.9  3587.5   161.1  3588.8   169.2 3589.56   177.2 3589.85
   192.2 3591.06   197.4 3592.27   206.5 3595.26   221.6 3598.96   246.1  3603.7
#Mann= 3 ,-1,0
       0      .1       0    64.5    .045       0    84.6      .1       0
#XS Ineff= 2 , 0
                          107.84         3599.16
Permanent Ineff=
       F       F
Bank Sta=64.5,84.6
XS Rating Curve= 0 ,0
Exp/Cntr(USF)=0,0
Exp/Cntr=0.3,0.1

Type RM Length L Ch R = 1 ,14814   ,167,165.4,163
XS GIS Cut Line= 2
2158949.75511278445844.914009229 2158996.2333323446104.772121978
#Sta/Elev= 30
       0 3608.59     4.3 3607.79    12.5 3607.05    16.5 3606.02    28.7 3600.63
    36.8 3596.55      49 3588.24    53.1 3586.96    61.2  3585.8    69.3 3581.16
    73.4  3580.1    85.6 3579.77   101.9 3579.84   118.1 3577.94   126.2 3577.56
   134.4 3577.89   146.6 3581.91   150.6 3582.69   166.9 3581.76   195.5 3581.85
   203.4 3582.66   211.6 3584.94   219.7 3586.55   223.8 3587.65   227.8 3589.59
   239.8 3598.27   244.1 3601.07   252.2  3605.6   256.3 3607.46     264 3611.63
#Mann= 3 ,-1,0
       0      .1       0   118.1    .045       0   134.4      .1       0
Bank Sta=118.1,134.4
XS Rating Curve= 0 ,0
Exp/Cntr(USF)=0,0
Exp/Cntr=0.3,0.1

Type RM Length L Ch R = 1 ,14649   ,192.3,205.6,214.5
XS GIS Cut Line= 2
2158808.16750596 445894.222883872158855.23942924446126.577909406
#Sta/Elev= 30
       0 3583.21     7.1 3582.43    23.4 3581.81    27.5 3581.09    35.7  3578.1
    39.7 3577.57    43.8 3578.31      52 3578.46    56.8  3577.6    64.2 3577.36
    72.4 3576.26    77.2 3576.63    97.5 3573.38   100.9 3572.97   109.1 3572.68
   113.2 3572.78   125.5 3575.16   131.5 3574.94   138.3 3573.75   141.8 3573.03
   145.9 3572.84     154 3572.98   157.3 3573.63   178.5 3578.31   185.8 3580.43
   190.8 3582.27   203.4 3585.47   211.2 3587.78   219.3 3591.99   237.1 3602.22
#Mann= 3 ,-1,0
       0      .1       0   138.3    .045       0   157.3      .1       0
Bank Sta=138.3,157.3
XS Rating Curve= 0 ,0
Exp/Cntr(USF)=0,0
Exp/Cntr=0.3,0.1

Type RM Length L Ch R = 1 ,14443   ,180.8,199.5,209.9
XS GIS Cut Line= 2
2158725.04049252445858.1677937012158608.86297975446041.447835395
#Sta/Elev= 30
       0 3579.43     3.6 3579.01      13 3576.57    22.5 3574.94    31.5  3572.5
    34.7 3571.97    41.5 3569.77    50.9 3567.83    55.7 3567.22    60.4 3567.51
    66.6 3568.59    74.6 3569.39    93.5 3569.29     103 3570.41   113.7 3570.98
   117.2 3570.81   121.7 3570.23   131.4 3567.67   136.1 3567.22   144.8 3567.21
   159.9 3567.56   169.3  3570.4   176.7 3577.11   178.8 3579.43   185.4 3588.35
   188.3 3591.56   194.1 3595.01   197.7 3597.44   210.8 3602.06     217 3605.06
#Mann= 3 ,-1,0
       0      .1       0   131.4    .045       0   159.9      .1       0
#XS Ineff= 2 , 0
          113.67 3578.14
Permanent Ineff=
       F       F
Bank Sta=131.4,159.9
XS Rating Curve= 0 ,0
Exp/Cntr(USF)=0,0
Exp/Cntr=0.3,0.1

Type RM Length L Ch R = 1 ,14244   ,208.3,196.9,184.8
XS GIS Cut Line= 2
2158715.02518969445799.0775070352158478.66404303445845.147900029
#Sta/Elev= 30
       0  3588.7     4.2 3587.98    15.1 3584.47    23.3 3582.33    31.5 3579.06
    38.3 3578.29    51.8  3577.5      60 3576.21    68.1 3575.54    72.2 3574.46
    86.1 3566.26    92.6 3563.42    96.6 3563.13   108.9 3559.73   112.9 3559.11
   121.1 3559.36   129.2 3558.52   137.2 3558.14   145.5 3558.35   149.6 3559.02
   154.3  3560.4   178.2 3568.46   190.4 3570.85   194.4 3571.24   198.6 3571.03
   202.6 3571.25   220.1 3573.94   225.9 3575.17   239.3 3579.27   240.8 3579.48
#Mann= 3 ,-1,0
       0      .1       0   129.2    .045       0   145.5      .1       0
Bank Sta=129.2,145.5
XS Rating Curve= 0 ,0
Exp/Cntr(USF)=0,0
Exp/Cntr=0.3,0.1

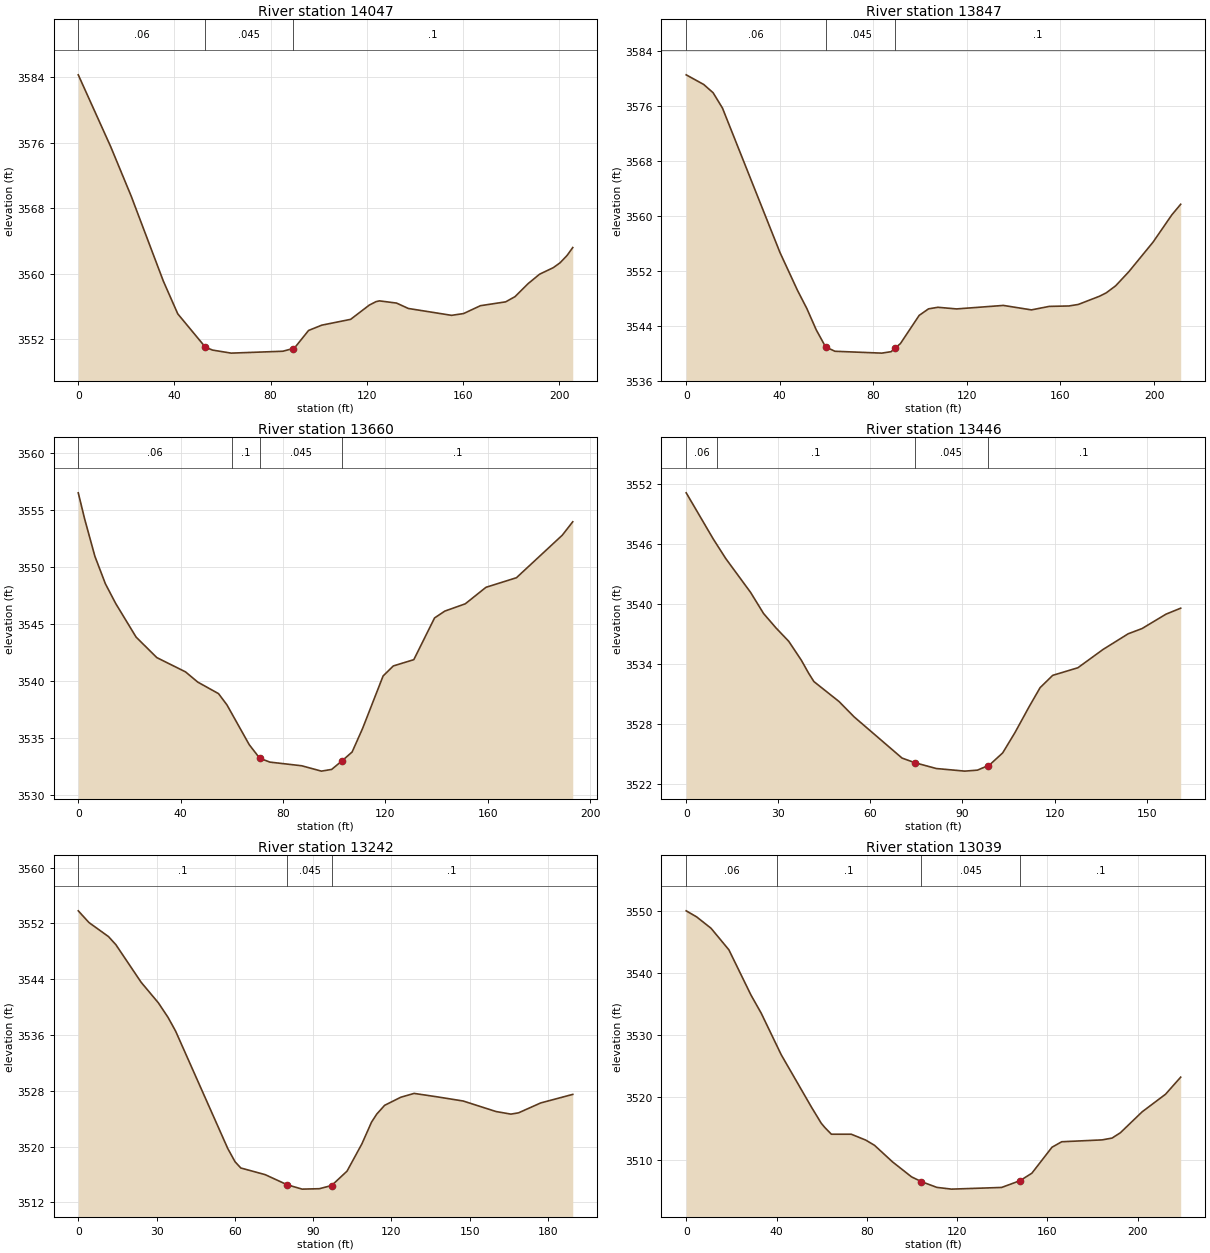
Type RM Length L Ch R = 1 ,14047   ,217.8,199.4,185
XS GIS Cut Line= 2
2158551.77575365445605.7821625162158414.56610495445759.016295735
#Sta/Elev= 30
       0 3584.31    13.5 3575.52      22 3569.49    35.4 3559.08    41.4 3555.08
    52.9    3551    55.9 3550.65    63.6 3550.28    85.1 3550.51    89.3 3550.84
    90.5 3551.11    95.8 3553.05   101.3  3553.7   113.3 3554.41   121.1 3556.16
   123.9 3556.58   125.3 3556.67   132.4  3556.4   137.3 3555.74   155.3  3554.9
   160.3 3555.12   167.3 3556.08   177.8 3556.55   181.7 3557.19   187.1 3558.77
   191.9 3559.93   197.6 3560.73   200.4 3561.32   203.3 3562.21   205.7 3563.19
#Mann= 3 ,-1,0
       0     .06       0    52.9    .045       0    89.3      .1       0
Bank Sta=52.9,89.3
XS Rating Curve= 0 ,0
Exp/Cntr(USF)=0,0
Exp/Cntr=0.3,0.1

Type RM Length L Ch R = 1 ,13847   ,182.1,187.4,187.2
XS GIS Cut Line= 2
2158319.42072811445517.6474976572158326.43144009445728.970387261
#Sta/Elev= 30
       0 3580.57     7.5 3579.16    11.5 3577.96    15.5 3575.73    40.1 3554.67
    47.6 3549.15    51.6  3546.5    55.6 3543.41    59.6 3540.92    63.6 3540.29
    83.6 3540.02    87.6 3540.23    89.4 3540.77    91.6 3541.42    99.6 3545.52
   103.6 3546.47   107.6  3546.7   115.6 3546.46   135.6 3546.97   147.6 3546.32
   155.2 3546.83   163.6 3546.89   167.6 3547.11   176.7 3548.31   179.6 3548.81
   183.6 3549.83   189.2 3551.87   199.6  3556.2   207.6 3560.16   211.4 3561.71
#Mann= 3 ,-1,0
       0     .06       0    59.6    .045       0    89.4      .1       0
Bank Sta=59.6,89.4
XS Rating Curve= 0 ,0
Exp/Cntr(USF)=0,0
Exp/Cntr=0.3,0.1

Type RM Length L Ch R = 1 ,13660   ,208.8,213.8,213.7
XS GIS Cut Line= 2
2158149.16058009445530.6673913292158130.13150472445722.961205566
#Sta/Elev= 30
       0 3556.48     2.5 3554.18     6.5 3550.91    10.6  3548.5    14.6 3546.78
    22.6 3543.82    30.7 3542.02    41.9 3540.77    46.7 3539.87    54.8 3538.86
    58.1 3537.87    66.8 3534.38    70.9 3533.19    74.9 3532.85    87.3 3532.53
      95 3532.06      99 3532.21     103 3532.95     107 3533.74   111.1 3535.81
   119.1 3540.41   123.1 3541.29   131.1 3541.84   139.2  3545.5   143.2  3546.1
   151.2 3546.74   159.3 3548.19   171.2 3549.03   189.1 3552.76   193.2 3553.94
#Mann= 4 ,-1,0
       0     .06       0      60      .1       0    70.9    .045       0
     103      .1       0
Bank Sta=70.9,103
XS Rating Curve= 0 ,0
Exp/Cntr(USF)=0,0
Exp/Cntr=0.3,0.1

Type RM Length L Ch R = 1 ,13446   ,198.5,204,210.3
XS GIS Cut Line= 2
2157956.86676585445484.5969983352157921.81320597445641.837252685
#Sta/Elev= 30
       0 3551.15     8.8 3546.54    12.9 3544.57      21 3541.18    25.2 3539.08
    29.3 3537.62    33.4  3536.3    37.5 3534.41    39.9  3533.1    41.6 3532.27
    49.8 3530.27    54.7 3528.74    70.3 3524.62    74.4 3524.16    81.5 3523.57
    90.8 3523.31    94.9 3523.41    98.2 3523.84      99 3523.98   103.1 3525.13
   107.1 3527.16   111.7 3529.74   115.3 3531.66   119.4 3532.89   127.6 3533.65
   135.8 3535.48     144 3537.05   148.5 3537.57   156.3 3539.01   161.1 3539.61
#Mann= 4 ,-1,0
       0     .06       0      10      .1       0    74.4    .045       0
    98.2      .1       0
Bank Sta=74.4,98.2
XS Rating Curve= 0 ,0
Exp/Cntr(USF)=0,0
Exp/Cntr=0.3,0.1

Type RM Length L Ch R = 1 ,13242   ,203.6,202.7,200.7
XS GIS Cut Line= 2
2157830.67395026445387.4485609342157716.49949806445538.679633589
#Sta/Elev= 30
       0 3553.81     4.1 3552.13    11.6 3550.11    14.4 3548.96    24.1 3543.56
    30.7 3540.61    34.4 3538.53    37.3 3536.56    57.3 3519.71    60.1 3517.81
    62.3 3516.92    71.6 3515.97    80.1 3514.51    85.8 3513.89    92.4 3513.95
    97.1 3514.41     103 3516.47   108.7 3520.39   112.4 3523.51   114.4 3524.66
   117.4 3525.91   123.6 3527.07   128.7 3527.62   137.5 3527.13   147.5 3526.53
   160.1 3525.02   165.8 3524.65   168.7 3524.83   177.2 3526.25   189.5 3527.48
#Mann= 3 ,-1,0
       0      .1       0    80.1    .045       0    97.1      .1       0
Bank Sta=80.1,97.1
XS Rating Curve= 0 ,0
Exp/Cntr(USF)=0,0
Exp/Cntr=0.3,0.1

Type RM Length L Ch R = 1 ,13039   ,214,213.3,211.2
XS GIS Cut Line= 2
2157644.38931772445291.3016538162157549.24394088445488.603119465
#Sta/Elev= 30
       0 3549.97     4.6    3549      11 3547.17    18.9 3543.71    28.7 3536.43
    33.2 3533.54    42.1 3526.84    55.4 3518.48    59.8 3515.85    61.5 3515.12
    64.3 3514.08    73.1 3514.08    79.5 3513.14    83.4  3512.3    91.4 3509.63
    99.8 3507.23   104.2 3506.46     111 3505.54   117.5 3505.26   139.7 3505.53
   147.8 3506.61   153.1 3507.82     162 3511.99   166.3 3512.87   184.2 3513.17
   188.6 3513.46   192.3 3514.32   201.9 3517.67   212.3 3520.51     219 3523.25
#Mann= 4 ,-1,0
       0     .06       0      40      .1       0   104.2    .045       0
   147.8      .1       0
Bank Sta=104.2,147.8
XS Rating Curve= 0 ,0
Exp/Cntr(USF)=0,0
Exp/Cntr=0.3,0.1

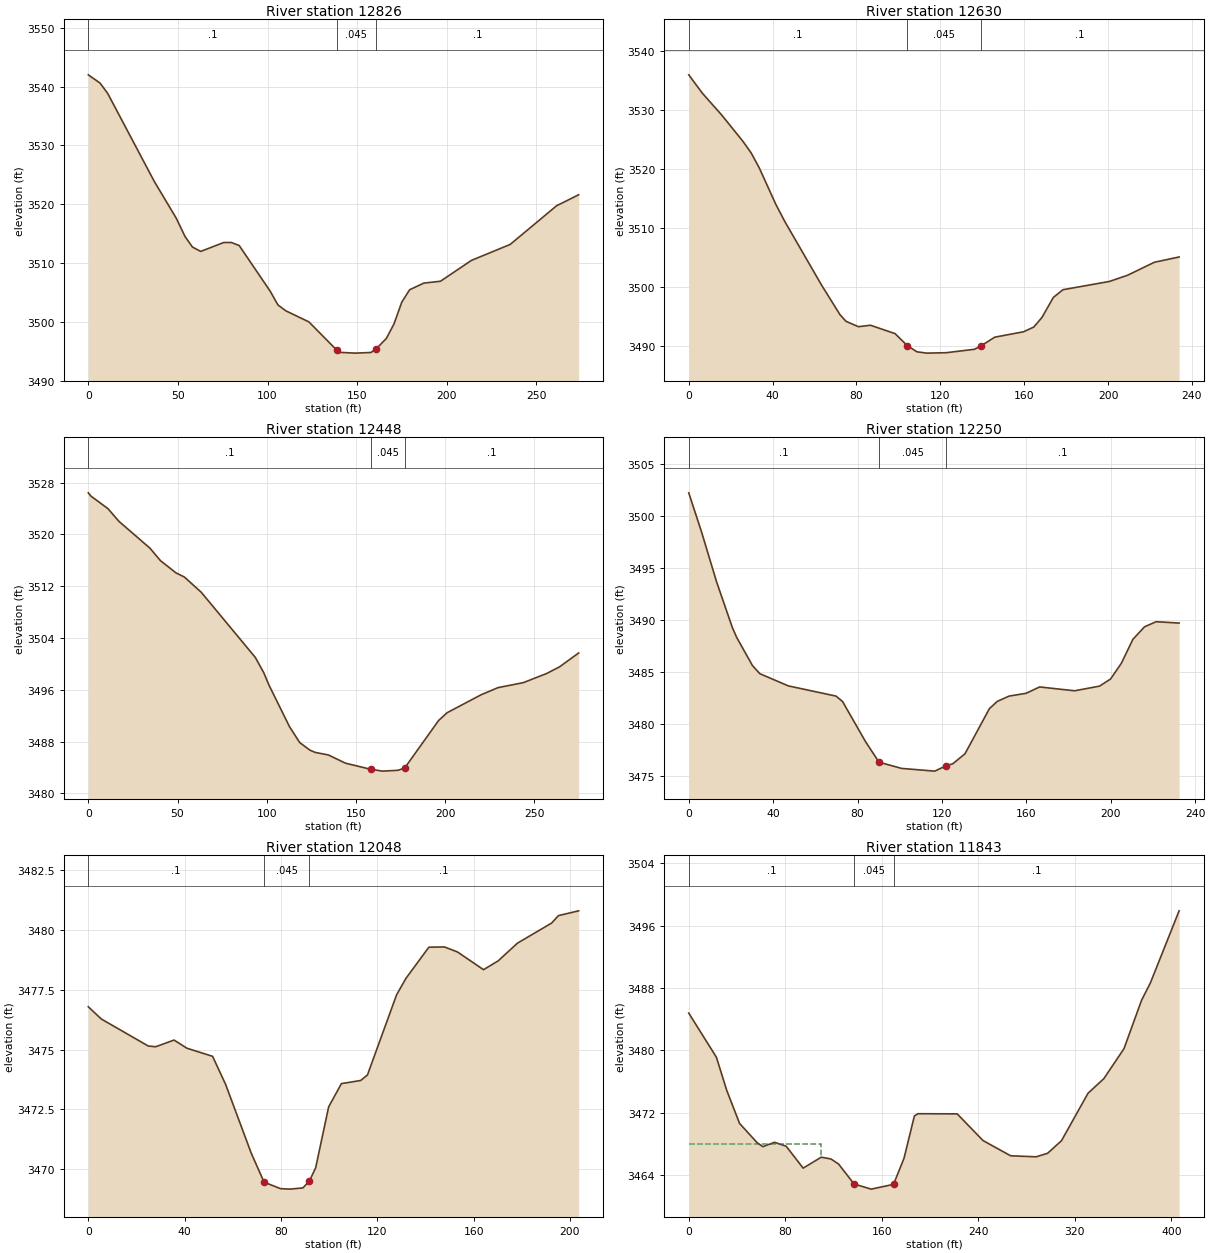
Type RM Length L Ch R = 1 ,12826   ,193.3,196.2,198.4
XS GIS Cut Line= 2
2157454.09856405445191.1486255682157350.94094495445444.535787036
#Sta/Elev= 30
       0 3542.02     6.5 3540.63    10.8 3538.87    36.7 3523.95    49.1 3517.61
      54  3514.5    58.1 3512.73    62.7 3511.98    75.6  3513.5    79.8  3513.5
    84.2 3512.98   101.5 3505.21   105.8 3502.88   110.2 3501.88   123.1 3499.99
   138.6  3495.2   140.4 3494.81     149 3494.68   157.7 3494.79   160.63495.395
   166.3 3497.18   170.6 3499.67   174.9 3503.35   179.3 3505.46   187.2 3506.59
   196.5 3506.91   213.8 3510.46   235.4 3513.17   261.3 3519.75   273.6 3521.62
#Mann= 3 ,-1,0
       0      .1       0   138.6    .045       0   160.6      .1       0
Bank Sta=138.6,160.6
XS Rating Curve= 0 ,0
Exp/Cntr(USF)=0,0
Exp/Cntr=0.3,0.1

Type RM Length L Ch R = 1 ,12630   ,184.4,182.3,183
XS GIS Cut Line= 2
2157297.31346184445119.5456566682157178.13135822445320.853243447
#Sta/Elev= 30
       0 3535.89     6.5 3532.78    15.8 3529.06    25.8 3524.67    29.8 3522.67
    33.6 3520.18    41.5 3514.02    45.8 3511.11    63.3 3500.38    72.1 3495.37
      75 3494.23    80.9 3493.32    86.7 3493.56    98.4 3492.15   104.3  3490.1
   108.8 3489.08   113.5 3488.85   122.8 3488.92   136.3  3489.5   139.3 3490.05
     146 3491.55   159.7 3492.46   164.6 3493.26   168.5 3494.89   173.9 3498.26
   178.5 3499.57   200.6 3500.96   209.3 3502.01   222.1 3504.21   233.9  3505.1
#Mann= 3 ,-1,0
       0      .1       0   104.3    .045       0   139.3      .1       0
Bank Sta=104.3,139.3
XS Rating Curve= 0 ,0
Exp/Cntr(USF)=0,0
Exp/Cntr=0.3,0.1

Type RM Length L Ch R = 1 ,12448   ,194.3,197.6,199.7
XS GIS Cut Line= 2
2157158.64713071445015.8808261342157010.42064891445247.234321387
#Sta/Elev= 30
       0 3526.41     1.5  3525.9      11 3523.97    17.2    3522    34.6 3517.85
    40.4 3515.95    49.1 3514.06    53.8 3513.42    63.3 3511.06    93.6    3501
    98.3 3498.66   101.3  3496.7   112.8 3490.29   118.5 3487.85   124.3 3486.67
   127.2 3486.34   134.6 3485.94   144.1 3484.68   158.3 3483.73   164.9 3483.45
   173.6 3483.58   177.3 3483.93   196.3 3491.26   201.1 3492.47   220.1 3495.23
   229.6 3496.34   243.8 3497.11   256.7  3498.5   264.1 3499.55   274.8 3501.69
#Mann= 3 ,-1,0
       0      .1       0   158.3    .045       0   177.3      .1       0
Bank Sta=158.3,177.3
XS Rating Curve= 0 ,0
Exp/Cntr(USF)=0,0
Exp/Cntr=0.3,0.1

Type RM Length L Ch R = 1 ,12250   ,202.3,202.2,201.1
XS GIS Cut Line= 2
2157010.42064891444936.7599338182156850.17580371445105.017021275
#Sta/Elev= 30
       0 3502.19     6.1 3498.41    13.2 3493.64    20.7 3489.24    22.7 3488.32
    30.2 3485.61    33.7 3484.83    47.2 3483.66    69.8 3482.68    72.9 3482.16
    83.9 3478.27    90.23476.334   100.9 3475.74   116.6 3475.48   122.1 3476.01
   125.1 3476.18   130.9 3477.14   142.5 3481.48   146.2 3482.17   151.8 3482.68
   159.9 3482.95   166.3 3483.56   182.9 3483.19   194.7 3483.64   199.9 3484.32
     205 3485.82   210.5 3488.13     216 3489.33   221.5 3489.82   232.4 3489.69
#Mann= 3 ,-1,0
       0      .1       0    90.2    .045       0   122.1      .1       0
Bank Sta=90.2,122.1
XS Rating Curve= 0 ,0
Exp/Cntr(USF)=0,0
Exp/Cntr=0.3,0.1

Type RM Length L Ch R = 1 ,12048   ,200.3,205.1,209.5
XS GIS Cut Line= 2
 2156845.1681523444814.5732393552156709.96156416444966.805842292
#Sta/Elev= 30
       0 3476.79     5.4 3476.28    24.9 3475.15      28 3475.12    35.6  3475.4
    40.9 3475.06    51.6 3474.72      57 3473.55    67.7 3470.66      73 3469.46
    79.8 3469.19    83.7 3469.17    89.1 3469.22    91.8 3469.51    94.4 3470.06
    99.8 3472.61   105.1 3473.58   113.1 3473.71   115.9 3473.94     128 3477.29
   131.9 3477.98   141.4 3479.28   147.9 3479.29   153.3 3479.08   164.1 3478.34
   170.2 3478.71   178.2 3479.45   192.4 3480.29   195.2  3480.6   203.6  3480.8
#Mann= 3 ,-1,0
       0      .1       0      73    .045       0    91.8      .1       0
Bank Sta=73,91.8
XS Rating Curve= 0 ,0
Exp/Cntr(USF)=0,0
Exp/Cntr=0.3,0.1

Type RM Length L Ch R = 1 ,11843   ,182.8,186.7,191.4
XS GIS Cut Line= 3
  2156759.036548444664.3436969822156544.70906755444809.565587942
2156460.58052382444930.750752123
#Sta/Elev= 30
       0 3484.78    22.9 3479.13    31.5 3474.87    42.1 3470.65    56.6 3468.19
    61.4 3467.67    71.1 3468.23    80.8 3467.72    94.8 3464.92   109.8 3466.32
   117.9 3466.09   124.2 3465.44     137 3462.89   151.2 3462.23   169.7 3462.84
   178.4 3466.18     187  3471.6   189.9 3471.89   222.5 3471.87   243.9 3468.45
   266.8  3466.5   287.9 3466.37   297.4 3466.82   308.9 3468.43   330.9 3474.51
     344 3476.38   360.7 3480.22   375.3 3486.43   382.6 3488.65   406.4 3497.88
#Mann= 3 ,-1,0
       0      .1       0     137    .045       0   169.7      .1       0
#XS Ineff= 2 , 0
       0   109.8    3468               0
Permanent Ineff=
       F       F
Bank Sta=137,169.7
XS Rating Curve= 0 ,0
Exp/Cntr(USF)=0,0
Exp/Cntr=0.3,0.1

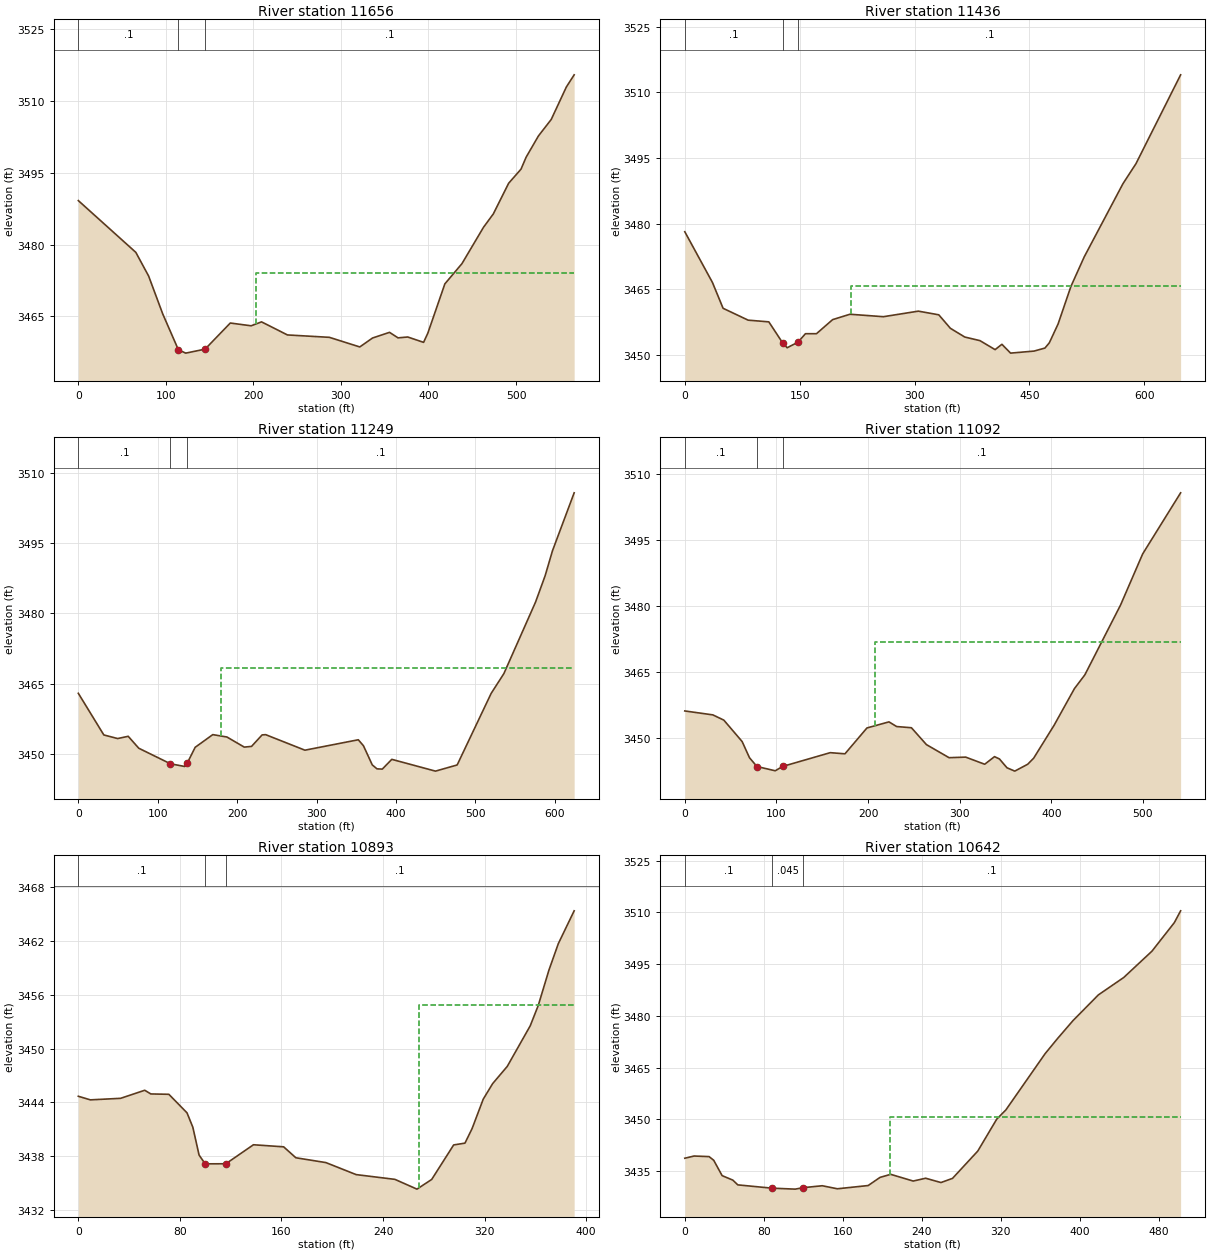
Type RM Length L Ch R = 1 ,11656   ,228.7,219.6,212.5
XS GIS Cut Line= 3
2156699.94626134444533.1432299772156506.65091682444601.247289186
2156301.33720891444898.701783083
#Sta/Elev= 30
       0 3489.21    65.7 3478.39    80.3 3473.45    96.4 3465.54   114.3 3458.04
   122.7 3457.34   144.83458.174   173.6 3463.63   197.4 3463.05   209.3 3463.87
   238.9 3461.14   286.8 3460.64   321.5 3458.63   336.1  3460.5   355.5 3461.68
   365.2 3460.53   376.3 3460.71   394.4 3459.59   399.3 3461.54   418.7 3471.81
   438.2 3476.03   462.8 3483.62   474.1 3486.44   491.6 3492.84   505.7 3495.78
   511.5 3498.27   525.6 3502.72   540.2 3506.16   557.5 3512.95   566.4 3515.49
#Mann= 3 ,-1,0
       0      .1       0   114.3    .045       0   144.8      .1       0
#XS Ineff= 2 , 0
                          203.16         3474.13
Permanent Ineff=
       F       F
Bank Sta=114.3,144.8
XS Rating Curve= 0 ,0
Exp/Cntr(USF)=0,0
Exp/Cntr=0.3,0.1

Type RM Length L Ch R = 1 ,11436   ,191.8,187.6,181.9
XS GIS Cut Line= 3
2156545.71059783444305.7958558542156355.41984416444496.086609526
2156086.00819817444761.492134383
#Sta/Elev= 30
       0 3478.13    36.1 3466.53      50 3460.62    82.7 3457.91   109.7 3457.52
   127.9 3452.67   133.6  3451.6   147.7 3452.86   157.5 3454.81   171.9 3454.81
     193 3458.03   215.6 3459.26   259.3  3458.7   304.9 3459.97   331.6 3459.13
   346.7 3456.05   365.5 3454.05   385.3 3453.23   405.1 3451.17     414 3452.39
   425.3 3450.37     456 3450.84   470.2 3451.53   475.9 3452.73   487.3 3457.02
   504.1 3465.63   521.5  3472.4     572 3489.11     589 3493.69   647.3 3514.01
#Mann= 3 ,-1,0
       0      .1       0   127.9    .045       0   147.7      .1       0
#XS Ineff= 2 , 0
                          216.39         3465.74
Permanent Ineff=
       F       F
Bank Sta=127.9,147.7
XS Rating Curve= 0 ,0
Exp/Cntr(USF)=0,0
Exp/Cntr=0.3,0.1

Type RM Length L Ch R = 1 ,11249   ,161.8,156.9,149.3
XS GIS Cut Line= 3
2156358.42443501444172.5923282842156246.25304337444405.948884102
2156003.88271501 444679.36665122
#Sta/Elev= 30
       0 3462.92    32.1 3454.01    49.5 3453.24    62.8 3453.72    76.1 3451.17
     116 3447.84   133.8 3447.27     137 3447.94   147.1 3451.36   169.3 3454.08
   187.1 3453.57   208.9 3451.41   218.1 3451.56   231.4 3454.02   235.9 3454.07
   285.3 3450.75   352.5 3452.98     359  3451.7   370.1  3447.6     376 3446.76
   382.7  3446.7   394.7 3448.79   449.7 3446.27     477 3447.59   519.8  3462.9
   535.8 3467.13   575.6  3482.4   587.7 3488.04     597 3493.41   624.3 3505.81
#Mann= 3 ,-1,0
       0      .1       0     116    .045       0     137      .1       0
#XS Ineff= 2 , 0
                          179.15         3468.27
Permanent Ineff=
       F       F
Bank Sta=116,137
XS Rating Curve= 0 ,0
Exp/Cntr(USF)=0,0
Exp/Cntr=0.3,0.1

Type RM Length L Ch R = 1 ,11092   ,190.5,198.6,203.5
XS GIS Cut Line= 3
2156158.11837851444186.6137522392156147.10154541444415.964186927
2155940.78630722444649.320742745
#Sta/Elev= 30
       0 3456.21    30.6 3455.32    42.6 3454.13    62.6 3449.26    70.6 3445.59
    78.7  3443.6    98.7 3442.63   106.7 3443.61   158.7 3446.74   174.8 3446.48
   198.8 3452.35   222.8 3453.73   231.2 3452.67   247.3  3452.4   263.7 3448.57
   288.4  3445.6   306.5 3445.73   327.3 3444.11     338 3445.84   343.4 3445.31
   351.6 3443.31   360.1 3442.55   374.2 3444.11   380.7 3445.48   403.1 3452.99
   425.2 3461.28   436.6 3464.41   475.6 3480.28   499.7 3491.87   541.1 3505.73
#Mann= 3 ,-1,0
       0      .1       0    78.7    .045       0   106.7      .1       0
#XS Ineff= 2 , 0
                          207.91         3471.79
Permanent Ineff=
       F       F
Bank Sta=78.7,106.7
XS Rating Curve= 0 ,0
Exp/Cntr(USF)=0,0
Exp/Cntr=0.3,0.1

Type RM Length L Ch R = 1 ,10893   ,245.8,251.5,251.5
XS GIS Cut Line= 2
2156032.81311254444129.1906787052155821.43627988 444457.49479264
#Sta/Elev= 30
       0 3444.69     9.5 3444.29    33.3 3444.46    52.3 3445.36    57.1 3444.95
    71.3 3444.91    85.6 3442.84    90.2 3441.23    95.1 3438.13    99.9 3437.15
   116.2 3437.16   137.9 3439.28   161.7 3439.05   171.3 3437.83     195 3437.29
   218.8 3435.95   249.3 3435.42   266.7 3434.33   278.3 3435.41   295.6 3439.26
   304.5 3439.46   310.1 3441.08   318.9 3444.37   326.3  3446.1   337.8 3448.02
   355.9 3452.55   362.2 3454.81   370.6 3458.75     378 3461.71   390.5 3465.38
#Mann= 3 ,-1,0
       0      .1       0    99.9    .045       0   116.2      .1       0
#XS Ineff= 2 , 0
                             268         3454.91
Permanent Ineff=
       F       F
Bank Sta=99.9,116.2
XS Rating Curve= 0 ,0
Exp/Cntr(USF)=0,0
Exp/Cntr=0.3,0.1

Type RM Length L Ch R = 1 ,10642   ,188.2,189.3,189.1
XS GIS Cut Line= 2
 2155827.6133853444051.4071641042155512.13134631444442.003974271
#Sta/Elev= 30
       0 3438.74     9.4 3439.38    24.6 3439.21    29.3 3438.14    37.8 3433.69
    48.6  3432.4    53.7 3431.01    88.2 3430.06   111.8 3429.78   120.1 3430.21
   139.2 3430.76   154.5 3429.88   185.7 3430.82   197.7 3433.18   208.5 3434.07
   231.3 3432.12   243.9 3432.94   259.4 3431.69   271.1  3432.9   296.7 3440.82
   315.9 3450.08   325.1 3452.73   364.9 3469.07   377.6 3473.49   393.1 3478.64
   418.8  3486.1   444.5 3491.15     473 3498.76   495.7 3507.04   502.1 3510.48
#Mann= 3 ,-1,0
       0      .1       0    88.2    .045       0   120.1      .1       0
#XS Ineff= 2 , 0
                          207.91         3450.77
Permanent Ineff=
       F       F
Bank Sta=88.2,120.1
XS Rating Curve= 0 ,0
Exp/Cntr(USF)=0,0
Exp/Cntr=0.3,0.1

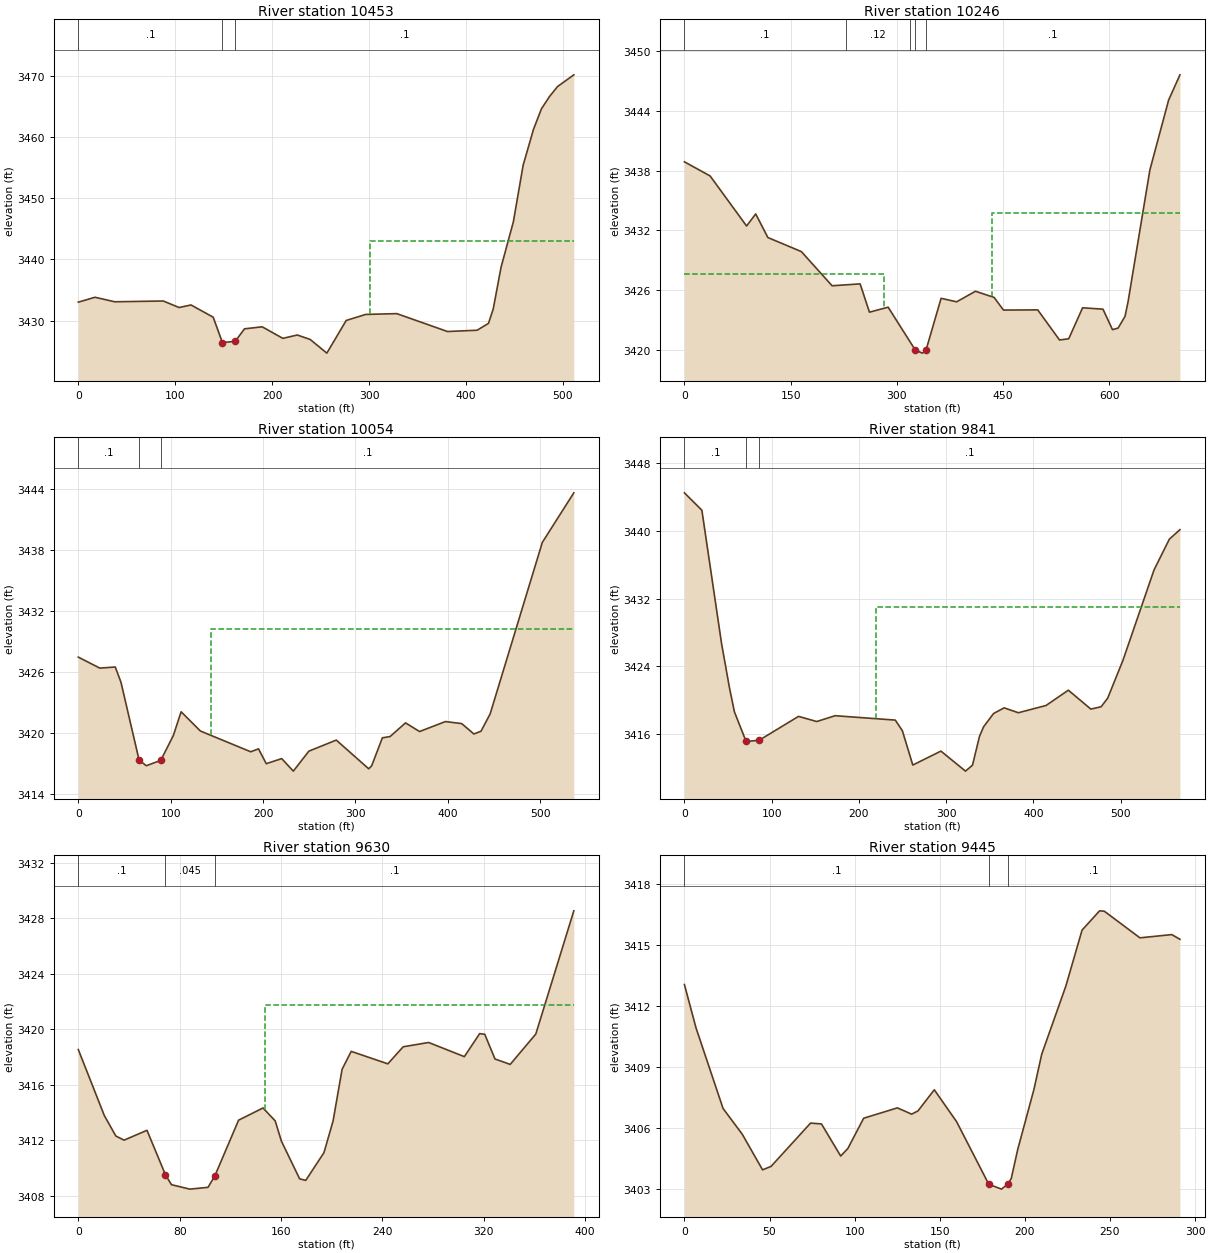
Type RM Length L Ch R = 1 ,10453   ,209,206.9,204.6
XS GIS Cut Line= 4
2155764.40932444443928.0613808412155660.10804506443958.474315013
2155534.28747877444130.5325193742155484.13041744444313.376306063
#Sta/Elev= 30
       0 3433.01    17.2 3433.81    37.7 3433.07    87.7  3433.2     104 3432.13
   116.3 3432.55   139.2 3430.55148.71913426.391161.91853426.591   171.5 3428.64
   189.8 3428.97   211.1 3427.08     226 3427.63   239.3  3426.9   256.5 3424.66
   276.5 3430.01   296.6    3431   328.7 3431.13     381  3428.2   411.6 3428.41
   423.3 3429.53   428.2 3431.87   436.3 3438.73     449 3446.17   459.1 3455.44
   469.7 3461.28     478 3464.69   486.3 3466.69   494.6 3468.33   511.4 3470.25
#Mann= 3 ,-1,0
       0      .1       0148.7191    .045       0161.9185      .1       0
#XS Ineff= 2 , 0
                          300.85         3443.06
Permanent Ineff=
       F       F
Bank Sta=148.7191,161.9185
XS Rating Curve= 0 ,0
Exp/Cntr(USF)=0,0
Exp/Cntr=0.3,0.1

Type RM Length L Ch R = 1 ,10246   ,193.3,192,189.9
XS GIS Cut Line= 3
2155697.99007189443725.1558228242155504.17146255443800.666493513
2155298.80539615 444247.70709947
#Sta/Elev= 30
       0 3438.89    36.3 3437.47    87.8 3432.45   100.7 3433.66   117.9 3431.29
   165.2 3429.88   208.6 3426.45   248.2 3426.64   261.4  3423.8   287.8  3424.3
326.14093419.999   336.2 3419.69341.24093419.979   362.6 3425.19   384.6 3424.84
   411.1  3425.9   437.5 3425.28   450.7 3424.01   499.1 3424.03   529.9 3421.01
   542.9 3421.13   562.5 3424.24   591.3  3424.1   604.7 3422.05   612.6  3422.2
   622.4 3423.37   626.8 3424.88   657.6 3438.09     684 3445.08     700 3447.62
#Mann= 5 ,-1,0
       0      .1       0  228.01     .12       0  318.01      .1       0
326.1409    .045       0341.2409      .1       0
#XS Ineff= 2 , 0
          282.37 3427.65  434.99         3433.76
Permanent Ineff=
       F       F
Bank Sta=326.1409,341.2409
XS Rating Curve= 0 ,0
Exp/Cntr(USF)=0,0
Exp/Cntr=0.3,0.1

Type RM Length L Ch R = 1 ,10054   ,222.1,212.7,198.1
XS GIS Cut Line= 3
2155299.80692643443762.9664427492155189.63859535444115.505102182
2155258.74418485 444267.73770512
#Sta/Elev= 30
       0 3427.46    23.3 3426.38      40 3426.49    46.2 3424.99    65.8 3417.35
    73.6 3416.79    89.3 3417.32   102.9 3419.76   111.3 3422.09   132.2  3420.2
   186.7 3418.16   195.1 3418.45   203.5 3416.99   220.2 3417.49   232.8 3416.26
   249.6 3418.22   279.3 3419.31   314.4 3416.49   317.6 3416.78   329.2 3419.53
   337.6 3419.66   354.3    3421   369.5 3420.15   397.5 3421.13   415.1 3420.93
   428.3 3419.91     436 3420.18   445.9 3421.88   502.4 3438.73   536.5  3443.6
#Mann= 3 ,-1,0
       0      .1       0    65.8    .045       0    89.3      .1       0
#XS Ineff= 2 , 0
                          143.32         3430.26
Permanent Ineff=
       F       F
Bank Sta=65.8,89.3
XS Rating Curve= 0 ,0
Exp/Cntr(USF)=0,0
Exp/Cntr=0.3,0.1

Type RM Length L Ch R = 1 ,9841    ,207.9,211.2,214
XS GIS Cut Line= 4
2155025.38762903443758.9603216192155139.56208123443874.136304104
2155166.60339886444117.5081627472155212.67379185 444271.74382625
#Sta/Elev= 30
       0 3444.51      20 3442.45    42.6 3426.65    51.6 3421.45    57.3 3418.59
    70.7 3415.08    85.6 3415.22   130.8 3418.05   151.7 3417.44   172.7 3418.13
   241.7 3417.61   249.8 3416.36   261.8 3412.29     294 3413.94   322.2 3411.57
   330.2 3412.27   338.3 3415.71     343 3416.83   354.4 3418.39   366.5 3419.06
   382.8 3418.48   414.5 3419.34   440.1 3421.15   465.9 3418.91   477.7 3419.19
   485.2 3420.21   502.7 3424.69   538.3 3435.38   555.9 3439.03     568 3440.15
#Mann= 3 ,-1,0
       0      .1       0    70.7    .045       0    85.6      .1       0
#XS Ineff= 2 , 0
                          220.06         3431.05
Permanent Ineff=
       F       F
Bank Sta=70.7,85.6
XS Rating Curve= 0 ,0
Exp/Cntr(USF)=0,0
Exp/Cntr=0.3,0.1

Type RM Length L Ch R = 1 ,9630    ,184.8,184.7,185
XS GIS Cut Line= 3
2154967.14242018443949.0754598142155147.30990178444070.090209356
2155167.17799499444243.032929785
#Sta/Elev= 30
       0 3418.52    20.5 3413.77    29.6 3412.29    36.1 3411.99    54.2  3412.7
    68.7 3409.51    73.5 3408.78      88 3408.46   102.4 3408.59   107.8 3409.42
   126.5 3413.43   145.8 3414.31   155.4 3413.38   160.3 3411.92   174.7  3409.2
   179.5 3409.09   193.9 3411.09   201.1 3413.38   208.2  3417.1   215.4 3418.39
   244.3 3417.49   256.4 3418.72   276.5 3419.03   304.7 3418.01   316.8 3419.67
   320.8 3419.62   328.9 3417.84   340.9 3417.45   361.1 3419.64   391.1 3428.52
#Mann= 3 ,-1,0
       0      .1       0    68.7    .045       0   107.8      .1       0
#XS Ineff= 2 , 0
                          147.15         3421.73
Permanent Ineff=
       F       F
Bank Sta=68.7,107.8
XS Rating Curve= 0 ,0
Exp/Cntr(USF)=0,0
Exp/Cntr=0.3,0.1

Type RM Length L Ch R = 1 ,9445    ,181.9,182.4,182.7
XS GIS Cut Line= 2
2154840.10452677444040.3903309962155046.41976496444245.704038905
#Sta/Elev= 30
       0 3413.07     6.8 3410.94    22.7 3406.97      34  3405.7    45.9 3403.95
    50.9 3404.12    74.1 3406.25    80.5 3406.21    91.8 3404.63      96    3405
   105.3 3406.49   125.1    3407   133.5 3406.69   137.2 3406.85   146.8 3407.89
   159.9 3406.32   178.8 3403.24   186.3    3403   190.1 3403.26     192 3403.52
   195.8 3404.95   205.3  3407.9   209.9 3409.64   224.1    3413   233.6 3415.75
   243.9  3416.7   246.7 3416.68   267.6 3415.37   286.3 3415.53   291.1  3415.3
#Mann= 3 ,-1,0
       0      .1       0   178.8    .045       0   190.1      .1       0
Bank Sta=178.8,190.1
XS Rating Curve= 0 ,0
Exp/Cntr(USF)=0,0
Exp/Cntr=0.3,0.1