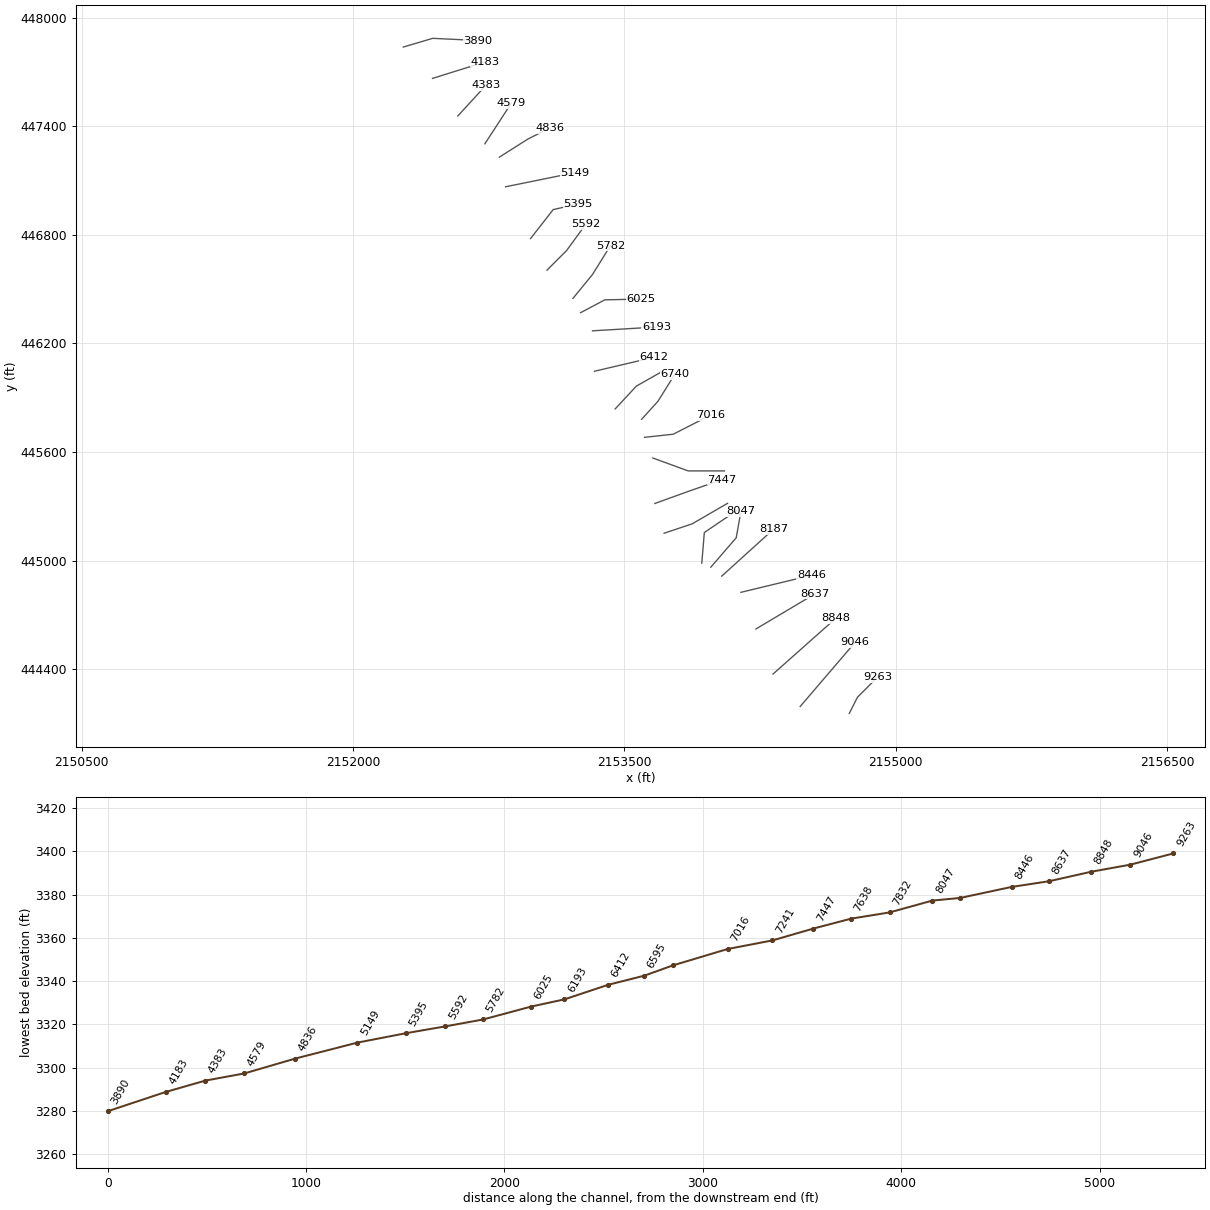
HEC-RAS study DOGWAYFK.prj: DOGWAYFK

--- DOGWAYFK.g01 (geometry) --- (continued)

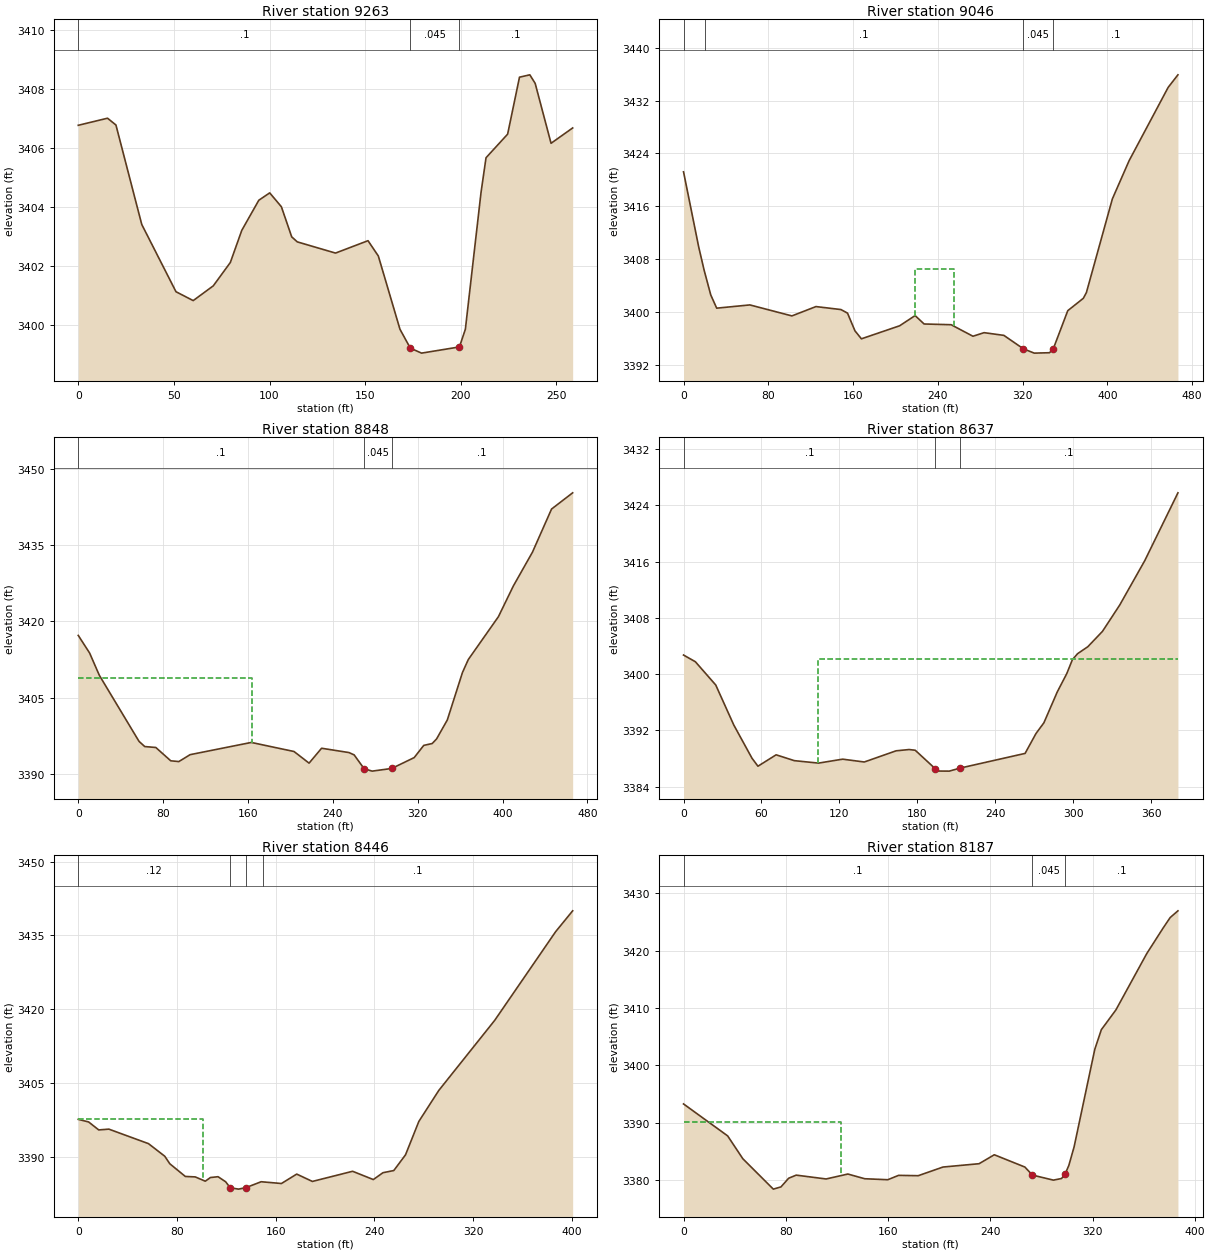
Type RM Length L Ch R = 1 ,9263    ,215,216.7,217.4
XS GIS Cut Line= 3
2154742.95608937444155.5663134822154788.02495208444244.702508623
2154900.19634372444356.873900261
#Sta/Elev= 30
       0 3406.76    15.3    3407    19.7 3406.77    33.2  3403.4    51.1 3401.12
    60.1 3400.82    70.6 3401.32    79.5 3402.11    85.5  3403.2    94.4 3404.22
   100.1 3404.47   106.2    3404   111.6 3402.98   114.5 3402.81   134.5 3402.43
   151.5 3402.85   156.9 3402.33   168.2 3399.85   173.6 3399.21   179.5 3399.04
   199.3 3399.25   202.4 3399.85   210.6 3404.49   213.2 3405.66   224.5 3406.46
   230.7 3408.39   236.1 3408.47   238.9 3408.18   247.2 3406.15   258.5 3406.67
#Mann= 3 ,-1,0
       0      .1       0   173.6    .045       0   199.3      .1       0
Bank Sta=173.6,199.3
XS Rating Curve= 0 ,0
Exp/Cntr(USF)=0,0
Exp/Cntr=0.3,0.1

Type RM Length L Ch R = 1 ,9046    ,200.4,198.1,194.4
XS GIS Cut Line= 2
2154471.54138282444193.6244642162154775.00505841444548.166184215
#Sta/Elev= 30
       0 3421.23    14.3  3409.9    19.4  3406.4    25.7 3402.64    31.3 3400.64
    62.6 3401.13   102.3 3399.47     125 3400.88   148.6 3400.43   154.8 3399.89
   161.8 3397.22   167.9 3396.01     204 3397.98   218.6 3399.52   227.1 3398.25
   252.6 3398.14   273.2  3396.4   283.7 3396.94   302.4 3396.53   320.8  3394.5
   331.1 3393.85   345.5 3393.91   349.1 3394.53   362.7 3400.26   377.4 3402.13
   380.3    3403   404.8 3417.14   420.6 3422.91   457.5 3433.99   466.7 3435.88
#Mann= 4 ,-1,0
       0     .12       0      20      .1       0   320.8    .045       0
   349.1      .1       0
#XS Ineff= 1 ,-1
  218.89  254.99 3406.57
Permanent Ineff=
       F
Bank Sta=320.8,349.1
XS Rating Curve= 0 ,0
Exp/Cntr(USF)=0,0
Exp/Cntr=0.3,0.1

Type RM Length L Ch R = 1 ,8848    ,214.5,211.3,208.7
XS GIS Cut Line= 2
2154321.31184044 444372.898384782154669.84437875444682.371242067
#Sta/Elev= 30
       0 3417.25    10.7 3413.79    19.9 3409.39    57.3 3396.41    62.7 3395.39
    73.1 3395.21    87.2 3392.59    94.8 3392.44   105.5  3393.8   163.1  3396.2
   203.4 3394.42   217.6 3392.13   229.4 3395.06   255.2 3394.21   260.1 3393.75
   269.5 3391.03   277.1 3390.56   295.6 3391.09   316.7 3393.22   325.7 3395.62
   333.7 3395.99   337.8 3396.89   347.9 3400.61   362.2 3409.95   367.7  3412.5
   396.1 3420.93   410.2 3426.98   428.2 3433.62   446.2  3442.1   466.1 3445.29
#Mann= 3 ,-1,0
       0      .1       0   269.5    .045       0   295.6      .1       0
#XS Ineff= 2 , 0
          163.38  3408.8
Permanent Ineff=
       F       F
Bank Sta=269.5,295.6
XS Rating Curve= 0 ,0
Exp/Cntr(USF)=0,0
Exp/Cntr=0.3,0.1

Type RM Length L Ch R = 1 ,8637    ,190.7,190,185.7
XS GIS Cut Line= 2
2154226.89811354 444622.027580812154554.03870296444816.660220512
#Sta/Elev= 30
       0  3402.7     9.1 3401.75    24.8 3398.44    38.7 3392.75    52.7 3388.03
    57.3 3386.89    71.3 3388.51    85.3 3387.68   103.9 3387.33   122.5 3387.89
   139.2 3387.49   163.7 3389.08   173.7 3389.26   178.4 3389.16193.93243386.516
     197  3386.2   204.6 3386.19213.12923386.627     263 3388.71   271.4 3391.54
   277.5 3393.07   287.8 3397.46   295.1 3400.06   299.4 3402.03   303.4 3402.89
   311.3 3403.88   322.6 3406.07   335.9 3409.82   355.2 3416.14   380.7 3425.77
#Mann= 3 ,-1,0
       0      .1       0193.9324    .045       0213.1292      .1       0
#XS Ineff= 1 ,-1
  103.23  103.23 3402.19
Permanent Ineff=
       F
Bank Sta=193.9324,213.1292
XS Rating Curve= 0 ,0
Exp/Cntr(USF)=0,0
Exp/Cntr=0.3,0.1

Type RM Length L Ch R = 1 ,8446    ,251.6,259.1,266.6
XS GIS Cut Line= 2
2154144.04098044 444824.588542182154533.63626033444918.732388733
#Sta/Elev= 30
       0 3397.69     8.4 3397.17    16.6 3395.55    24.8 3395.71    56.9 3392.77
    70.1 3390.22    74.2 3388.69    86.8 3386.11    94.8 3386.02     103 3385.15
   107.1 3385.89   113.3 3386.06   119.5 3385.03   123.2 3383.82   129.9 3383.54
   135.9 3383.84   148.3 3385.04   164.7 3384.68   177.1 3386.59   189.8  3385.1
   222.4 3387.16   239.2 3385.48     247 3386.87   255.8 3387.31   265.3  3390.5
   276.1 3397.27   292.3 3403.57   337.6 3417.78     387 3435.77   400.8    3440
#Mann= 4 ,-1,0
       0     .12       0   123.2    .045       0   135.9     .12       0
     150      .1       0
#XS Ineff= 2 , 0
          100.85 3397.69
Permanent Ineff=
       F       F
Bank Sta=123.2,135.9
XS Rating Curve= 0 ,0
Exp/Cntr(USF)=0,0
Exp/Cntr=0.3,0.1

Type RM Length L Ch R = 1 ,8187    ,127.6,139.9,147.7
XS GIS Cut Line= 2
2154037.81280342444914.0245952042154324.36444487445173.558802016
#Sta/Elev= 30
       0  3393.3    34.5 3387.73    46.4 3383.74    70.2 3378.45    76.2 3378.84
    82.2 3380.35    88.1 3380.89   111.5 3380.22   128.5 3381.08   141.7 3380.26
   159.7 3380.09   168.2 3380.85   183.5 3380.79   202.9  3382.3   231.1 3382.88
     243 3384.44   266.9  3382.3   272.8  3380.9   289.2 3380.02   295.6  3380.3
   298.4 3381.08   301.3 3382.59   305.4 3385.81   321.6 3402.84   326.7 3406.24
   338.1 3409.69   362.2  3419.5   374.9 3423.92   380.5 3425.78   386.6 3426.96
#Mann= 3 ,-1,0
       0      .1       0   272.8    .045       0   298.4      .1       0
#XS Ineff= 2 , 0
          123.49 3390.11
Permanent Ineff=
       F       F
Bank Sta=272.8,298.4
XS Rating Curve= 0 ,0
Exp/Cntr(USF)=0,0
Exp/Cntr=0.3,0.1

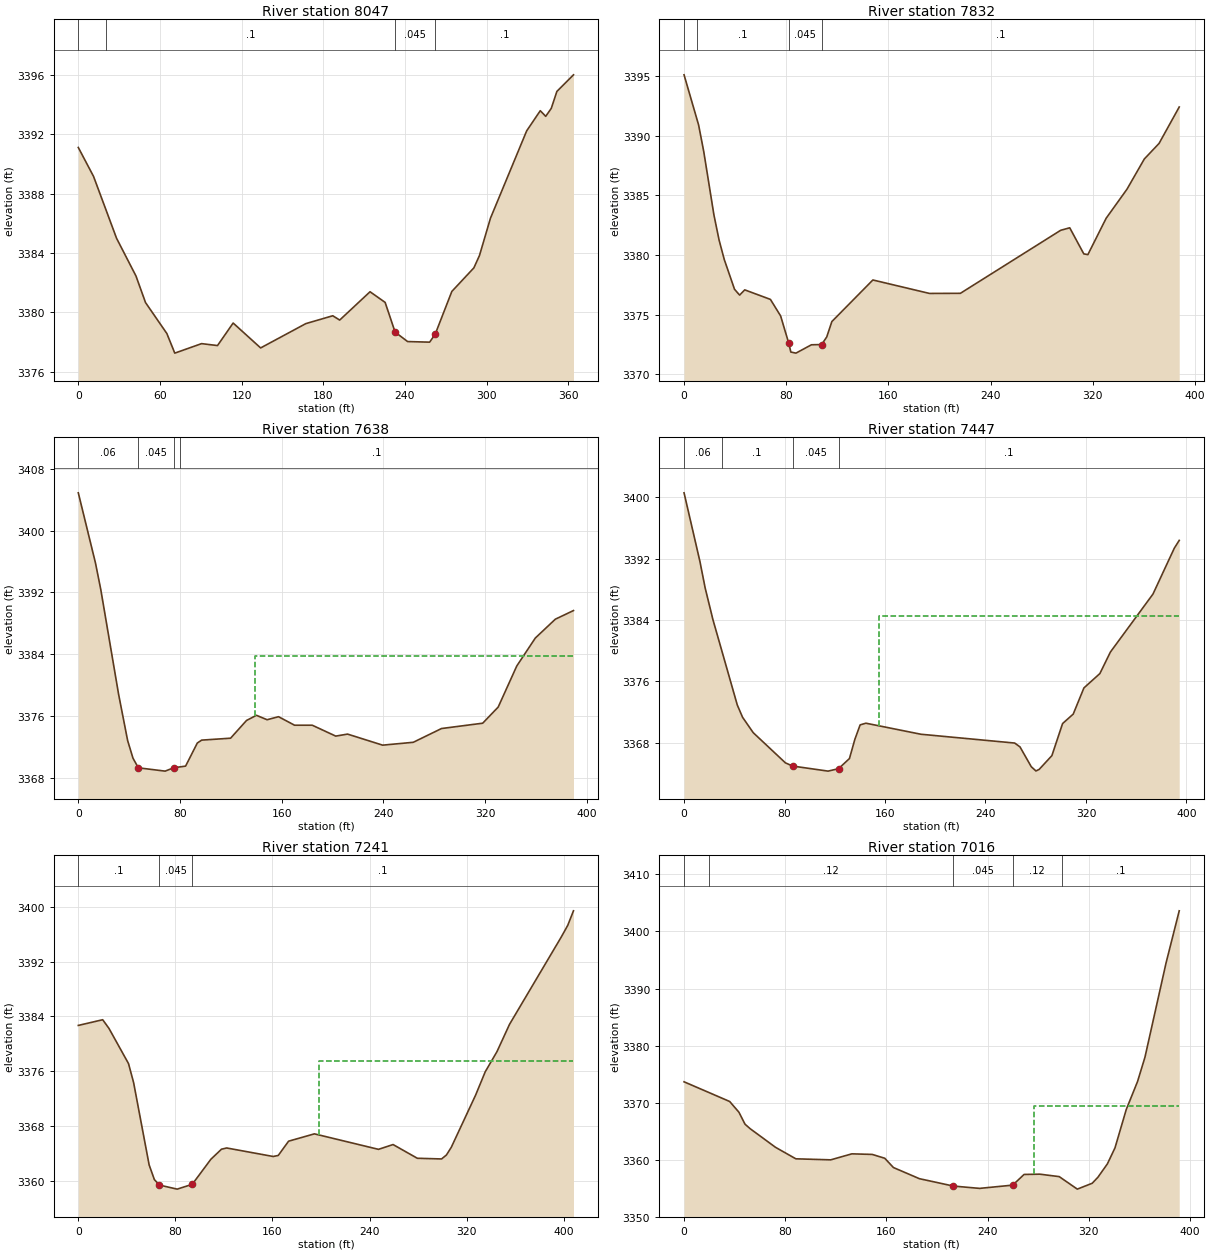
Type RM Length L Ch R = 1 ,8047    ,205.7,215.7,215
XS GIS Cut Line= 3
2153977.78695355444963.801251445 2154118.0011931445126.049157207
2154144.04098044445273.274108732
#Sta/Elev= 30
       0 3391.11    11.2 3389.16    28.1 3384.99    42.4 3382.44    49.4 3380.65
    65.1 3378.56    70.9 3377.24    90.6 3377.88   102.3 3377.75   113.8 3379.27
     134 3377.59   167.2 3379.23     187 3379.76   192.1 3379.47   214.4 3381.38
   225.5 3380.66   232.8 3378.66     242 3378.02   258.2 3377.98   262.3 3378.52
   274.5  3381.4   290.7 3382.99   294.8 3383.82   302.9 3386.34   329.5 3392.23
   339.5 3393.59   343.5 3393.21   347.6 3393.75   351.7 3394.89   363.9 3396.01
#Mann= 4 ,-1,0
       0     .12       0      20      .1       0   232.8    .045       0
   262.3      .1       0
Bank Sta=232.8,262.3
XS Rating Curve= 0 ,0
Exp/Cntr(USF)=0,0
Exp/Cntr=0.3,0.1

Type RM Length L Ch R = 1 ,7832    ,211.1,193.7,175.4
XS GIS Cut Line= 3
2153927.71043943444985.8349176592153941.73186338445155.093535399
2154122.00731423445277.280229862
#Sta/Elev= 30
       0 3395.12    11.4 3390.91    15.4 3388.69    23.4 3383.35    27.4 3381.26
    31.5 3379.61    39.5 3377.12    43.5 3376.63    47.5 3377.07    67.6 3376.27
    75.6 3374.88    81.9 3372.61    83.6 3371.85    87.6 3371.76    99.7 3372.46
   107.7 3372.48   111.7 3373.12   115.7 3374.41   147.8  3377.9   192.1 3376.77
   216.3 3376.78   294.8 3382.07   301.9 3382.28   312.9 3380.09   316.1 3380.03
   330.4 3383.08   346.7 3385.52   360.3 3388.06   371.8 3389.36   387.6 3392.42
#Mann= 4 ,-1,0
       0     .12       0      10      .1       0    81.9    .045       0
   107.7      .1       0
Bank Sta=81.9,107.7
XS Rating Curve= 0 ,0
Exp/Cntr(USF)=0,0
Exp/Cntr=0.3,0.1

Type RM Length L Ch R = 1 ,7638    ,182.4,190.6,186.7
XS GIS Cut Line= 3
2153719.39214067445151.0874142692153874.62933446445203.166988958
2154069.92773954445316.339910878
#Sta/Elev= 30
       0 3404.89    13.5 3395.82    17.7 3392.37    31.7 3378.83    38.8 3372.85
      43 3370.57    47.2 3369.32    68.3 3368.89    74.9 3369.32    84.4 3369.54
    93.6 3372.52      97  3372.9   119.8 3373.15   132.3 3375.44   140.1 3376.11
   148.5 3375.54   157.5 3375.93   170.1 3374.83     184 3374.83   202.5 3373.42
   211.8 3373.68   239.4 3372.25   263.5 3372.62   285.7  3374.4   318.1 3375.09
   330.3 3377.18   344.9 3382.49   359.5 3386.11   375.2 3388.54   389.5 3389.66
#Mann= 4 ,-1,0
       0     .06       0    47.2    .045       0    74.9     .06       0
      80      .1       0
#XS Ineff= 2 , 0
                          138.89         3383.82
Permanent Ineff=
       F       F
Bank Sta=47.2,74.9
XS Rating Curve= 0 ,0
Exp/Cntr(USF)=0,0
Exp/Cntr=0.3,0.1

Type RM Length L Ch R = 1 ,7447    ,221.3,206.7,196.1
XS GIS Cut Line= 3
 2153668.3440738445315.5123163252153847.58801683445380.437848957
2154039.88183107445447.540377883
#Sta/Elev= 30
       0 3400.59    12.6 3391.67    16.8 3388.19      23 3384.05    42.4 3372.92
    46.6 3371.32    55.1 3369.31    80.7 3365.3886.434013364.962   114.7  3364.3
123.00673364.619   131.7 3365.94     136 3368.44   140.2 3370.33   144.8 3370.55
   188.6 3369.11   263.3 3367.96   267.5 3367.46   276.5 3364.87   280.2 3364.32
   282.8 3364.53   292.9 3366.32   301.4  3370.5   309.9 3371.74   318.4 3375.15
   331.1 3377.02   339.5 3379.83   373.4 3387.39   390.4 3393.38   394.3 3394.39
#Mann= 4 ,-1,0
       0     .06       0      30      .1       086.43401    .045       0
123.0067      .1       0
#XS Ineff= 2 , 0
                             155         3384.48
Permanent Ineff=
       F       F
Bank Sta=86.43401,123.0067
XS Rating Curve= 0 ,0
Exp/Cntr(USF)=0,0
Exp/Cntr=0.3,0.1

Type RM Length L Ch R = 1 ,7241    ,199.1,224.7,237.1
XS GIS Cut Line= 3
2153657.29726316445566.7224814992153852.59566824445495.613831443
2154052.90172474445495.613831443
#Sta/Elev= 30
       0 3382.68    20.1 3383.51    25.3 3382.24    41.4 3377.11    45.6 3374.33
    58.4 3362.33    62.7  3360.2    66.9  3359.4    81.5 3358.81    93.9 3359.51
   109.3 3363.17     118 3364.63   122.3 3364.81   160.6 3363.57   164.8 3363.72
   173.3  3365.8   194.6 3366.87   247.4 3364.61   259.4 3365.31   279.4 3363.31
   299.4 3363.21   303.4 3363.79   307.4 3364.91   327.4  3372.5   335.4 3375.93
     345 3378.84   355.4 3382.84   397.9 3395.53   403.4 3397.28   408.1 3399.39
#Mann= 3 ,-1,0
       0      .1       0    66.9    .045       0    93.9      .1       0
#XS Ineff= 2 , 0
                          198.42         3377.44
Permanent Ineff=
       F       F
Bank Sta=66.9,93.9
XS Rating Curve= 0 ,0
Exp/Cntr(USF)=0,0
Exp/Cntr=0.3,0.1

Type RM Length L Ch R = 1 ,7016    ,217.5,276,235.1
XS GIS Cut Line= 3
 2153612.2524485445681.2987482172153770.00248601445698.426719652
2153977.49310768 445804.36698029
#Sta/Elev= 30
       0 3373.67      20 3371.76    36.1 3370.22    43.4 3368.34    48.2 3366.25
    52.2 3365.47    72.3  3362.2    88.4 3360.18     116    3360   132.7 3361.05
   148.8 3360.95   158.7 3360.28   165.6 3358.65   186.1  3356.7   212.9 3355.41
   233.7    3355   259.9 3355.57   268.9 3357.44   281.3 3357.49   296.7 3357.06
     311 3354.87   322.8  3355.9   327.3 3356.95   334.8  3359.3   340.8  3362.1
   349.7 3368.81   358.6  3373.7   364.5 3377.98   381.2 3394.51   391.6 3403.62
#Mann= 5 ,-1,0
       0      .1       0      20     .12       0   212.9    .045       0
   259.9     .12       0  298.68      .1       0
#XS Ineff= 2 , 0
                          277.11         3369.45
Permanent Ineff=
       F       F
Bank Sta=212.9,259.9
XS Rating Curve= 0 ,0
Exp/Cntr(USF)=0,0
Exp/Cntr=0.3,0.1

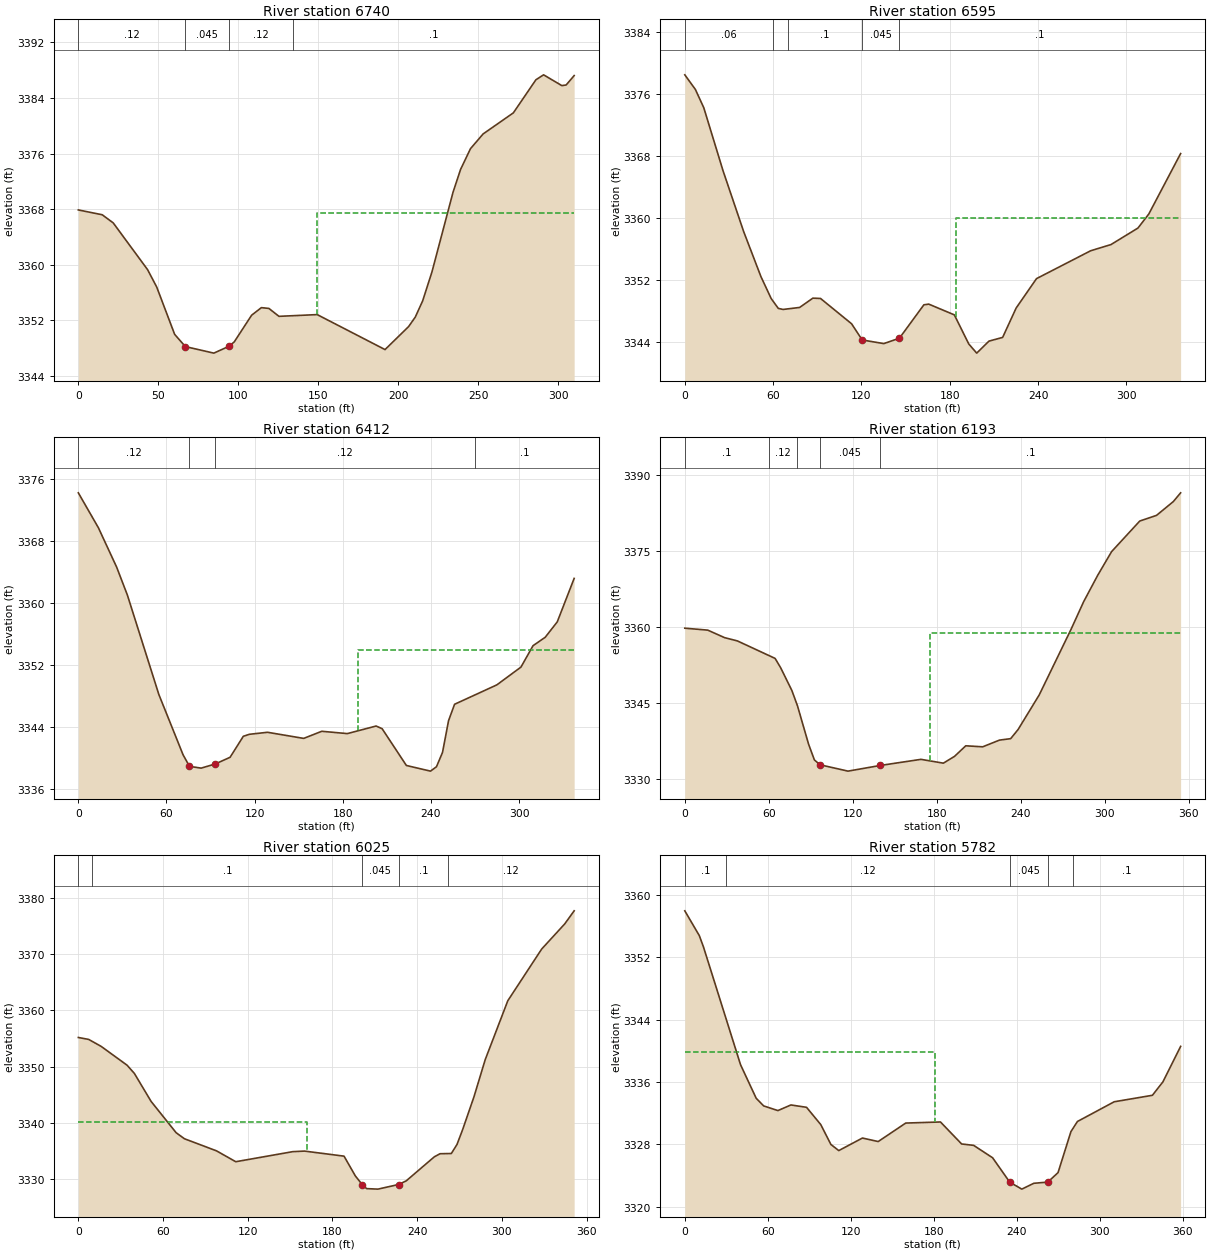
Type RM Length L Ch R = 1 ,6740    ,145.7,145.3,145.2
XS GIS Cut Line= 3
2153595.20238564 445781.049961952153685.34011107445880.201459916
2153778.48242734446029.429472005
#Sta/Elev= 30
       0 3367.89    14.9  3367.2    21.8 3366.03    43.3  3359.3      49  3356.8
    60.2    3350    66.9 3348.24    84.7  3347.3    94.2 3348.29    97.5 3348.93
   108.3 3352.75   114.4 3353.84   119.1 3353.73   125.4 3352.59   149.3 3352.84
   191.7 3347.81   206.4 3351.11   210.6 3352.48   215.2 3354.81     221 3358.96
   234.2 3370.44   238.9 3373.71   245.1  3376.7     253 3378.82   271.9 3381.85
     286 3386.61   290.8 3387.32   302.2 3385.77   304.9 3385.86   309.9 3387.21
#Mann= 4 ,-1,0
       0     .12       0    66.9    .045       0    94.2     .12       0
     134      .1       0
#XS Ineff= 2 , 0
                          149.07          3367.4
Permanent Ineff=
       F       F
Bank Sta=66.9,94.2
XS Rating Curve= 0 ,0
Exp/Cntr(USF)=0,0
Exp/Cntr=0.3,0.1

Type RM Length L Ch R = 1 ,6595    ,188.6,182.5,172.9
XS GIS Cut Line= 3
 2153448.9789644445838.1371880512153566.15800745445964.330003644
2153709.37683785446045.453956525
#Sta/Elev= 30
       0 3378.45     7.2 3376.56    12.9  3374.2      26 3366.05      40  3358.2
    51.7  3352.4    58.7 3349.55    63.5 3348.29    66.7 3348.15      78 3348.41
      87 3349.61    92.2 3349.57   113.3  3346.3   120.5 3344.21   135.2 3343.74
   145.8 3344.44   162.4 3348.75   165.7 3348.84   183.1 3347.45   192.9 3343.69
   198.3 3342.51   206.6 3344.06   215.9 3344.54   225.1 3348.34   238.9 3352.13
   275.7 3355.73   289.5 3356.53   307.8 3358.66   315.2 3360.48   336.8 3368.28
#Mann= 5 ,-1,0
       0     .06       0      60     .12       0      70      .1       0
   120.5    .045       0   145.8      .1       0
#XS Ineff= 2 , 0
                          183.97         3359.96
Permanent Ineff=
       F       F
Bank Sta=120.5,145.8
XS Rating Curve= 0 ,0
Exp/Cntr(USF)=0,0
Exp/Cntr=0.3,0.1

Type RM Length L Ch R = 1 ,6412    ,219,219.4,215.1
XS GIS Cut Line= 2
 2153334.8045122446046.4554868082153663.44439103446123.495327448
#Sta/Elev= 30
       0 3374.25    13.7 3369.72    26.1 3364.64    33.4 3361.03    54.8 3348.19
    71.3 3340.3975.655613338.895    83.6 3338.6793.229163339.204   103.3 3340.07
   112.3 3342.78   116.4 3343.04   128.8  3343.3   153.4 3342.51   165.7 3343.43
   183.1 3343.13   202.7 3344.11   206.8 3343.76   223.3 3339.01   239.7 3338.28
   243.8 3338.85   247.9  3340.7     252  3344.8   256.1 3346.92   284.9 3349.43
   301.3 3351.73   309.5 3354.49   317.8 3355.58     326 3357.57   337.5 3363.19
#Mann= 4 ,-1,0
       0     .12       075.65561    .045       093.22916     .12       0
     270      .1       0
#XS Ineff= 2 , 0
                          190.28            3354
Permanent Ineff=
       F       F
Bank Sta=75.65561,93.22916
XS Rating Curve= 0 ,0
Exp/Cntr(USF)=0,0
Exp/Cntr=0.3,0.1

Type RM Length L Ch R = 1 ,6193    ,168.1,168,165.9
XS GIS Cut Line= 2
2153323.78767909446269.7967398012153677.32786881446290.828875733
#Sta/Elev= 30
       0 3359.74    16.4 3359.36    28.4 3357.88    37.6 3357.23    64.5 3353.79
    68.5 3351.94    76.5 3347.46    80.5 3344.44    88.5 3336.83    92.6 3333.78
    96.6 3332.83   116.6 3331.58   139.7  3332.7   168.7  3333.9   184.7 3333.15
   192.7 3334.49   200.7 3336.57   212.8 3336.37   224.8 3337.69   232.8 3337.98
   238.1 3339.78   253.2  3346.6   275.9  3359.5   284.9 3364.95     295 3370.18
   304.9 3374.83     325 3380.85     337 3381.97     349 3384.69   354.2 3386.41
#Mann= 5 ,-1,0
       0      .1       0      60     .12       0      80      .1       0
    96.6    .045       0   139.7      .1       0
#XS Ineff= 2 , 0
                          175.12         3358.73
Permanent Ineff=
       F       F
Bank Sta=96.6,139.7
XS Rating Curve= 0 ,0
Exp/Cntr(USF)=0,0
Exp/Cntr=0.3,0.1

Type RM Length L Ch R = 1 ,6025    ,226.3,242.3,254.4
XS GIS Cut Line= 3
2153257.68668045446369.949768049 2153391.8917383446441.058418105
2153591.19626451446445.064539235
#Sta/Elev= 30
       0 3355.19     7.3 3354.85    16.1 3353.62    34.5 3350.27    39.7  3348.8
    51.6 3343.81    69.3 3338.26    75.2 3337.19    97.9 3335.04   111.5 3333.11
   151.9  3334.9   160.2    3335   188.2  3334.1   196.2 3330.59  201.053329.058
   204.2 3328.33   212.2 3328.24   226.8 3329.06   232.2  3329.7   252.2 3333.99
   256.2 3334.53   264.2 3334.57   268.2 3336.17   272.2 3338.81   280.2 3344.62
   288.2 3351.25   304.2 3361.72   328.2 3370.91   344.5 3375.37   351.2  3377.7
#Mann= 5 ,-1,0
       0     .12       0      10      .1       0  201.05    .045       0
   226.8      .1       0  261.88     .12       0
#XS Ineff= 2 , 0
          162.19 3340.24
Permanent Ineff=
       F       F
Bank Sta=201.05,226.8
XS Rating Curve= 0 ,0
Exp/Cntr(USF)=0,0
Exp/Cntr=0.3,0.1

Type RM Length L Ch R = 1 ,5782    ,191.2,190.7,189.4
XS GIS Cut Line= 3
2153215.62240858446449.0706603652153323.78767909446581.272657653
2153422.93917706446740.515972567
#Sta/Elev= 30
       0 3357.95    10.5 3354.77    13.5 3353.32    40.3 3338.22    51.6 3333.92
      57 3332.94    67.3 3332.34    76.7 3333.06      88 3332.76    98.3 3330.54
   105.6    3328   111.3 3327.21   128.4 3328.82   139.8 3328.37   159.7 3330.74
   184.8 3330.88   200.1 3328.06   208.8 3327.88   222.5 3326.29   234.9 3323.16
   243.6 3322.27   252.3 3323.02   262.4 3323.17   269.8 3324.39   279.1 3329.64
   283.8 3330.94   310.4 3333.47     338  3334.3   345.6 3336.02   358.4 3340.57
#Mann= 5 ,-1,0
       0      .1       0      30     .12       0   234.9    .045       0
   262.4     .12       0  280.81      .1       0
#XS Ineff= 2 , 0
          181.16 3339.88
Permanent Ineff=
       F       F
Bank Sta=234.9,262.4
XS Rating Curve= 0 ,0
Exp/Cntr(USF)=0,0
Exp/Cntr=0.3,0.1

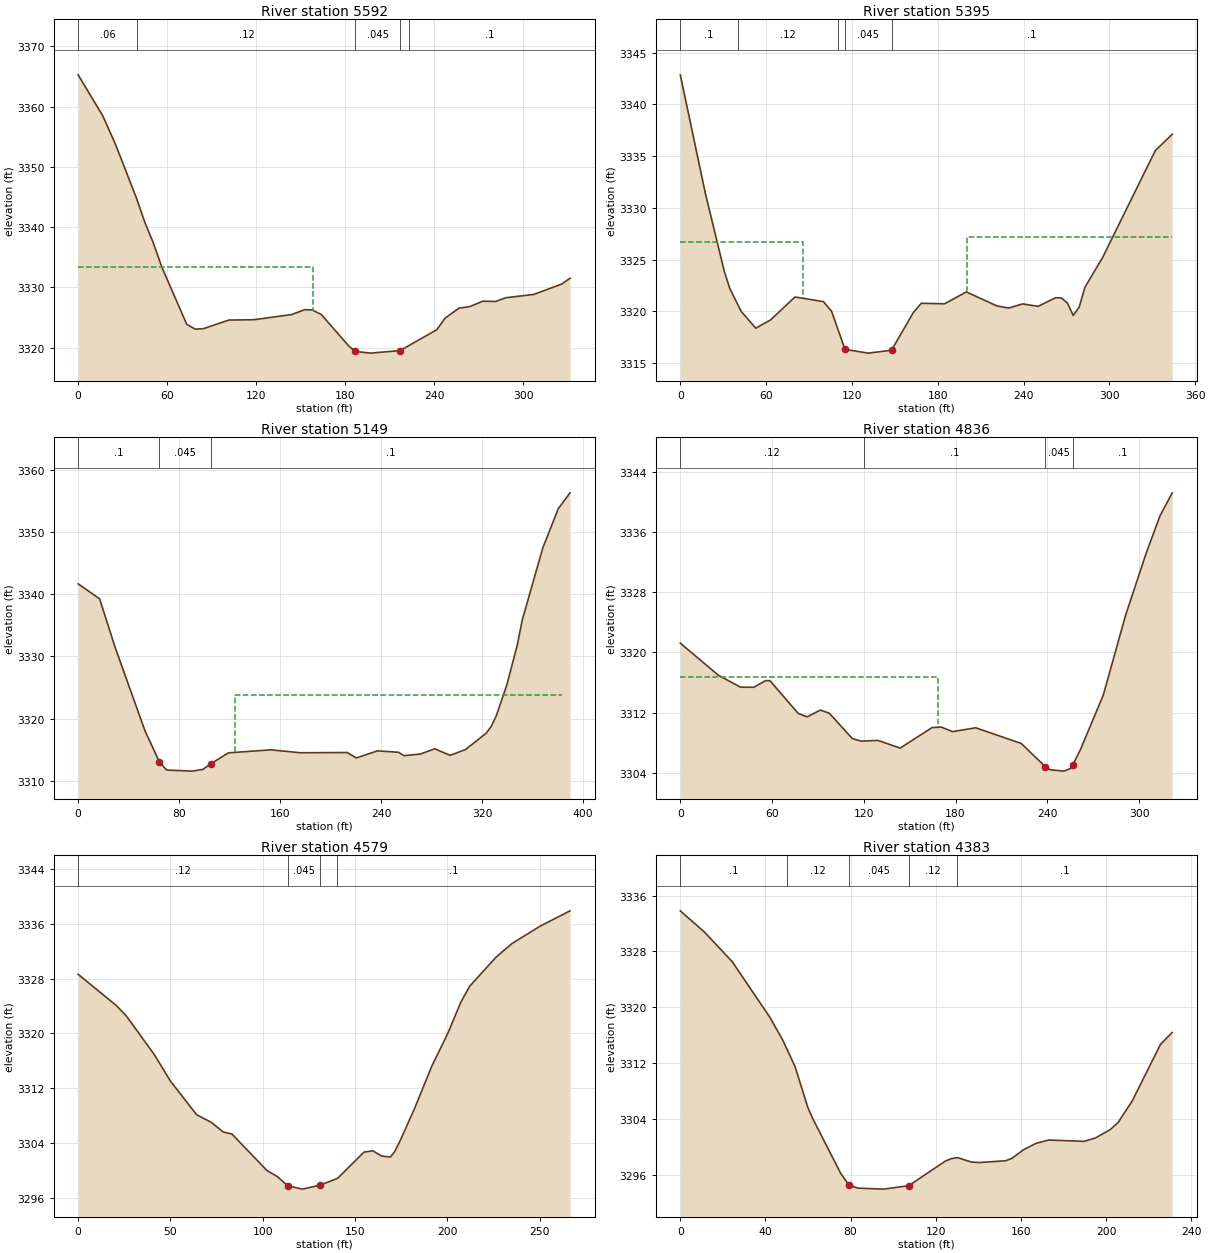
Type RM Length L Ch R = 1 ,5592    ,197.1,197.1,196.5
XS GIS Cut Line= 3
2153072.40357819446605.309384432 2153180.5688487 446713.47465494
2153285.72952836446857.695015618
#Sta/Elev= 30
       0 3365.28    16.6 3358.47    25.2 3353.73    39.3 3344.82    45.1 3340.69
    50.7 3337.35    56.4 3333.36    73.2 3323.86    78.9 3323.06    84.5 3323.15
   101.6 3324.57   118.6 3324.63     144 3325.49   152.6 3326.29   157.6 3326.26
   163.9 3325.49   182.3 3320.28   186.8 3319.36   197.2 3319.08     217 3319.51
   241.7 3322.96   247.3 3324.89   256.6 3326.54   264.1 3326.82   272.7  3327.7
   281.4 3327.66   288.1 3328.27   307.1 3328.83   325.9 3330.55   331.5 3331.52
#Mann= 5 ,-1,0
       0     .06       0      40     .12       0   186.8    .045       0
     217     .12       0  222.97      .1       0
#XS Ineff= 2 , 0
          158.52 3333.34
Permanent Ineff=
       F       F
Bank Sta=186.8,217
XS Rating Curve= 0 ,0
Exp/Cntr(USF)=0,0
Exp/Cntr=0.3,0.1

Type RM Length L Ch R = 1 ,5395    ,265.6,245.7,235.1
XS GIS Cut Line= 3
2152981.26432248446779.5756535842153106.45560779446939.820498781
2153243.66525649446970.867937538
#Sta/Elev= 30
       0 3342.86    17.5 3331.41    30.7  3323.9    34.6  3322.2    42.6 3319.98
    52.8 3318.36    63.2 3319.17    80.2 3321.38   100.1 3320.93   105.8 3319.99
   115.2 3316.31   131.5 3315.95   147.7 3316.23   162.8 3319.84   168.5 3320.77
   184.8 3320.72     200 3321.87   221.5 3320.51   229.7 3320.31   239.4 3320.71
   250.2 3320.47   262.5 3321.31   266.6 3321.28   270.7 3320.79   274.8 3319.59
   278.9 3320.39     283 3322.33   295.3 3325.19   332.2 3335.54     344 3337.11
#Mann= 5 ,-1,0
       0      .1       0      40     .12       0     110      .1       0
   115.2    .045       0   147.7      .1       0
#XS Ineff= 2 , 0
           85.55 3326.67  200.54         3327.16
Permanent Ineff=
       F       F
Bank Sta=115.2,147.7
XS Rating Curve= 0 ,0
Exp/Cntr(USF)=0,0
Exp/Cntr=0.3,0.1

Type RM Length L Ch R = 1 ,5149    ,306.4,312.8,306.6
XS GIS Cut Line= 2
2152843.49094757447065.8993337162153225.27188644447143.586903698
#Sta/Elev= 30
       0 3341.68      17 3339.27    29.3 3331.46      53 3318.0364.354793313.081
    70.1 3311.75    90.5 3311.58    98.7 3311.85   105.1 3312.77   119.1 3314.52
   152.6    3315   176.2 3314.53     213 3314.57   220.4  3313.7   237.1 3314.84
   253.8 3314.61     258 3314.06   271.3 3314.34   282.4 3315.17   294.6 3314.12
   306.8 3315.05   323.2 3317.67   327.3  3318.8   331.3 3320.53   339.5 3325.41
   347.7 3331.76   351.7 3335.83   368.1 3347.49   380.3 3353.76   389.6  3356.3
#Mann= 3 ,-1,0
       0      .1       064.35479    .045       0   105.1      .1       0
#XS Ineff= 1 ,-1
  123.94   383.1 3323.85
Permanent Ineff=
       F
Bank Sta=64.35479,105.1
XS Rating Curve= 0 ,0
Exp/Cntr(USF)=0,0
Exp/Cntr=0.3,0.1

Type RM Length L Ch R = 1 ,4836    ,246.3,257.3,261.3
XS GIS Cut Line= 3
2152809.15709612447229.7964991022152966.24136824447329.415778667
2153087.42653243447390.509125898
#Sta/Elev= 30
       0 3321.22    24.9 3316.96    39.4 3315.37    48.1 3315.36    55.7 3316.24
    58.6 3316.24    77.1 3311.89    82.9 3311.43    91.6 3312.33    97.4 3311.92
   112.5 3308.55   118.3  3308.2   129.3  3308.3   143.8 3307.28   164.6    3310
   170.6 3310.08   178.1 3309.46   193.2 3309.98     223 3307.89238.76193304.805
   241.9  3304.4   250.9 3304.22   255.4 3304.59256.56193305.006   261.7 3307.09
   276.6 3314.31   291.2 3324.92   304.6 3333.13   313.6 3338.08   321.7 3341.19
#Mann= 4 ,-1,0
       0     .12       0     120      .1       0238.7619    .045       0
256.5619      .1       0
#XS Ineff= 2 , 0
          168.28 3316.66
Permanent Ineff=
       F       F
Bank Sta=238.7619,256.5619
XS Rating Curve= 0 ,0
Exp/Cntr(USF)=0,0
Exp/Cntr=0.3,0.1

Type RM Length L Ch R = 1 ,4579    ,198.4,196.3,193.2
XS GIS Cut Line= 2
 2152728.8786913447303.3759913222152874.10058226447526.717244316
#Sta/Elev= 30
       0 3328.62    20.7 3324.06      26 3322.59    41.3  3316.9    50.1 3313.02
    64.2 3308.16    72.1 3307.06    78.5 3305.66    83.3 3305.35   102.3 3300.03
   107.8 3299.17   113.6 3297.81   121.4 3297.33   130.8 3297.89   140.5  3298.9
   154.8 3302.72   159.6 3302.91   164.4 3302.14   169.1 3302.01   171.4 3302.78
   174.3 3304.33   182.2 3309.08   191.6 3315.28   200.3 3320.08   207.3 3324.59
   212.1 3326.89   226.2 3331.08     235 3333.11   250.3 3335.64   266.4 3337.86
#Mann= 4 ,-1,0
       0     .12       0   113.6    .045       0   130.8     .12       0
     140      .1       0
Bank Sta=113.6,130.8
XS Rating Curve= 0 ,0
Exp/Cntr(USF)=0,0
Exp/Cntr=0.3,0.1

Type RM Length L Ch R = 1 ,4383    ,208.1,199.3,189.9
XS GIS Cut Line= 2
2152579.65067921447457.6116548252152735.88940327447627.871802846
#Sta/Elev= 30
       0 3333.81    11.4 3330.76    24.4 3326.54    42.2 3318.54    48.2 3315.28
    53.9 3311.56    59.9 3305.72    62.3 3304.06    75.4 3296.26    79.3 3294.59
    83.6 3294.17    95.4 3294.03   107.3 3294.52   124.6 3298.05   127.5  3298.4
   130.3 3298.53   136.8  3297.9   140.6 3297.83   152.9 3298.09   155.8 3298.43
   161.4 3299.69   167.1 3300.57   173.1 3301.05   189.7 3300.86   194.9 3301.33
   201.9 3302.52   205.7 3303.56   212.4 3306.68   225.6 3314.73   231.1 3316.42
#Mann= 5 ,-1,0
       0      .1       0      50     .12       0    79.3    .045       0
   107.3     .12       0     130      .1       0
Bank Sta=79.3,107.3
XS Rating Curve= 0 ,0
Exp/Cntr(USF)=0,0
Exp/Cntr=0.3,0.1

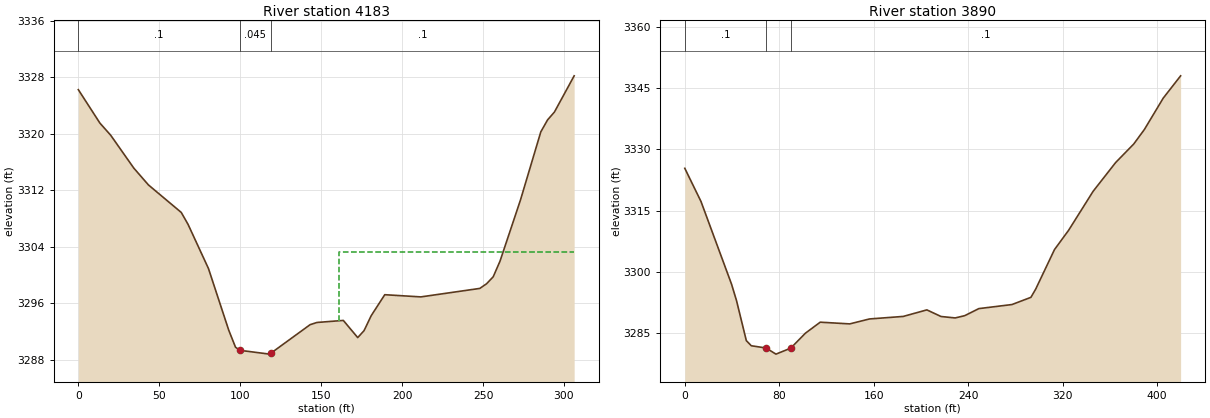
Type RM Length L Ch R = 1 ,4183    ,291.5,293.5,290.1
XS GIS Cut Line= 2
2152439.43643966447664.9284232982152731.88328214447756.067679004
#Sta/Elev= 30
       0 3326.21    13.3 3321.49      20 3319.76    34.3  3315.1    43.3 3312.73
    63.6 3308.83    67.8 3307.14    80.4 3300.89    92.9 3292.18    97.1 3289.76
    99.8 3289.32   118.1 3288.78     119 3288.92   143.2 3292.95   147.4 3293.26
   163.7 3293.55   172.6 3291.12   176.5  3292.1   180.9 3294.21   189.3 3297.19
   211.6 3296.88     248 3298.08   252.2 3298.74   256.3 3299.73   260.5 3301.94
   273.1 3310.57   285.7 3320.24   289.9 3321.94   294.1 3323.04   306.3 3328.17
#Mann= 3 ,-1,0
       0      .1       0    99.8    .045       0     119      .1       0
#XS Ineff= 2 , 0
                          161.29          3303.3
Permanent Ineff=
       F       F
Bank Sta=99.8,119
XS Rating Curve= 0 ,0
Exp/Cntr(USF)=0,0
Exp/Cntr=0.3,0.1

Type RM Length L Ch R = 1 ,3890    ,115.6,117,117.3
XS GIS Cut Line= 3
2152278.19006418447838.1931621682152440.43796994447886.266615727
2152690.82054056447874.248252337
#Sta/Elev= 30
       0 3325.35    13.7 3317.24    39.6 3296.98    43.8 3292.97    52.1 3283.17
    56.3 3281.91    68.8 3281.36    77.2 3279.86    89.7 3281.32   102.2    3285
   114.7 3287.68   139.7 3287.26   156.4 3288.47     185 3289.09     205 3290.69
     217 3289.07     229 3288.72     237 3289.27     249    3291   277.1    3292
   293.1 3293.76   297.1 3295.74   313.1 3305.46   325.1  3310.2   345.8 3319.72
   364.9 3326.77   380.2  3331.3   389.2 3334.85   405.2 3342.54   419.9 3347.99
#Mann= 3 ,-1,0
       0      .1       0    68.8    .045       0    89.7      .1       0
Bank Sta=68.8,89.7
XS Rating Curve= 0 ,0
Exp/Cntr(USF)=0,0
Exp/Cntr=0.3,0.1