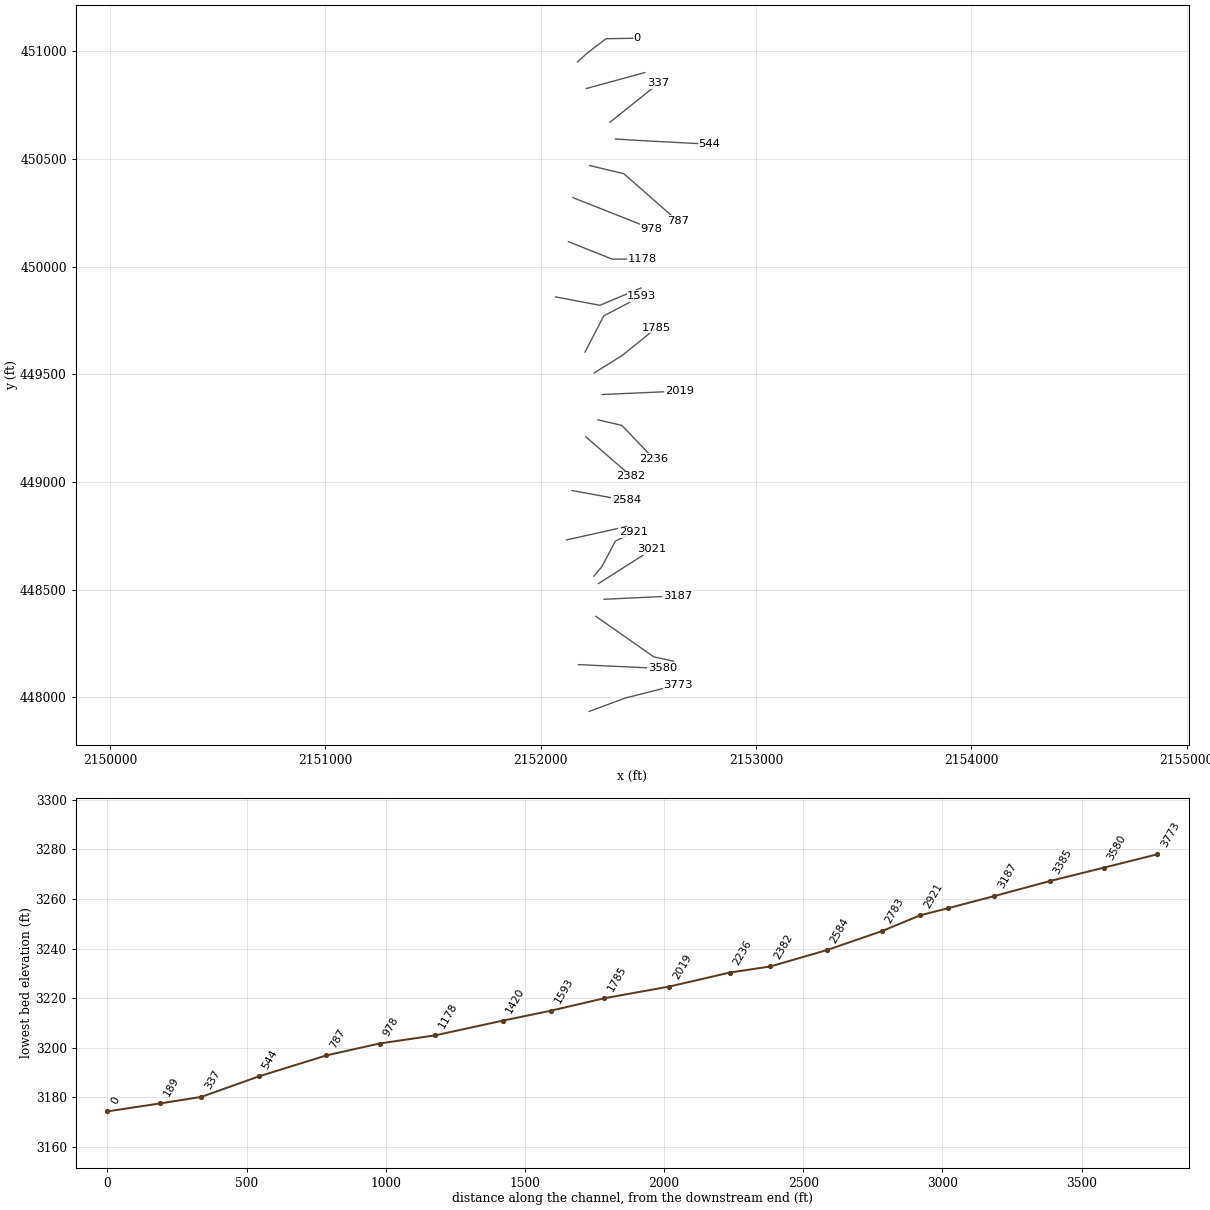
HEC-RAS study DOGWAYFK.prj: DOGWAYFK

--- DOGWAYFK.g01 (geometry) --- (continued)

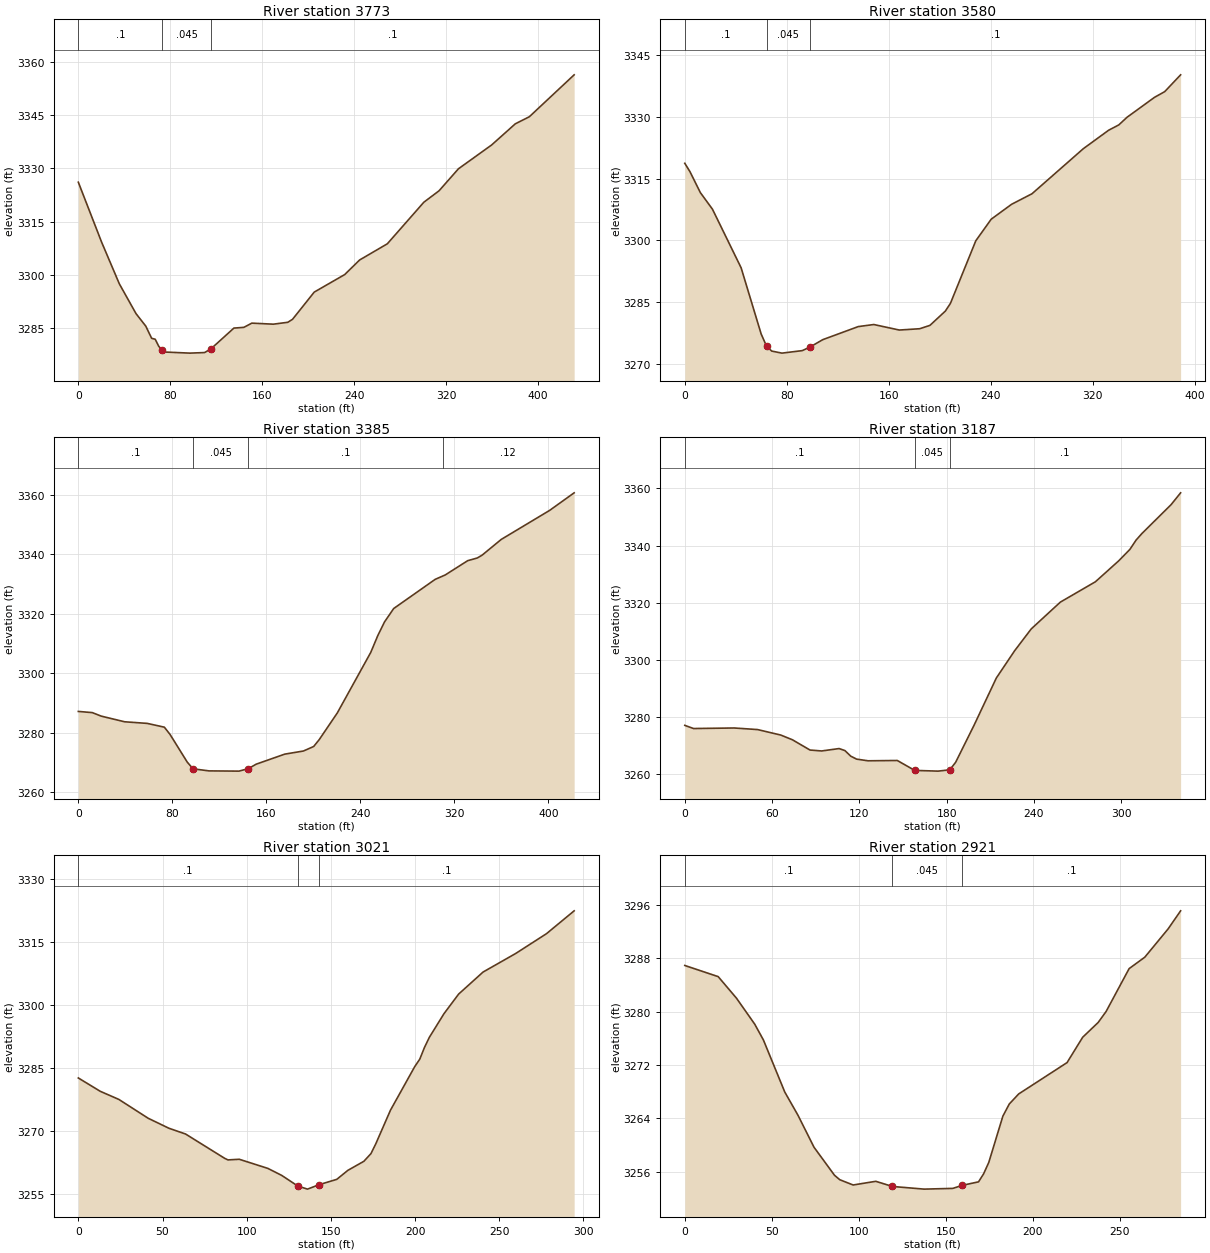
Type RM Length L Ch R = 1 ,3773    ,198.1,192.6,183.9
XS GIS Cut Line= 3
2152225.10895921447934.3400692862152393.36604666  447996.4349468
2152637.73943559448058.529824314
#Sta/Elev= 30
       0 3326.09    20.3 3309.19    35.7 3297.48    50.2  3289.1    58.7 3285.58
    63.8 3282.15    66.9 3281.89      70 3279.89    73.1 3278.78    75.8 3278.28
    97.1 3277.98   109.9 3278.14   115.3 3279.15   135.4 3285.03     144 3285.23
     151 3286.42   169.7 3286.13   182.3 3286.66   186.4 3287.49   205.3 3295.16
   231.8 3300.09   244.8  3304.2   268.9 3308.75   300.7 3320.46   313.9 3323.67
   330.8 3329.87   359.7 3336.58   380.3 3342.53   392.5 3344.52   431.5 3356.32
#Mann= 3 ,-1,0
       0      .1       0    73.1    .045       0   115.3      .1       0
Bank Sta=73.1,115.3
XS Rating Curve= 0 ,0
Exp/Cntr(USF)=0,0
Exp/Cntr=0.3,0.1

Type RM Length L Ch R = 1 ,3580    ,202.8,195.2,182.5
XS GIS Cut Line= 2
2152176.03397537448151.6721405852152564.62772497  448133.6445955
#Sta/Elev= 30
       0 3318.72     4.1 3316.66    12.2  3311.6    21.7 3307.57    44.2 3293.32
    59.9 3277.25    64.2 3274.23    68.2 3273.09    76.2 3272.59    92.2  3273.2
    98.2 3274.07   108.3 3275.87   136.1 3279.04   148.3 3279.54   168.3  3278.2
   184.3 3278.52   192.3 3279.33   204.4  3282.8   208.4 3284.68   228.3 3299.89
   240.4 3305.14   256.4 3308.76   272.4 3311.32   312.7 3322.28   332.5 3326.75
   340.5 3328.05   346.9 3329.89   368.5 3334.75   376.5 3336.13     389 3340.22
#Mann= 3 ,-1,0
       0      .1       0    64.2    .045       0    98.2      .1       0
Bank Sta=64.2,98.2
XS Rating Curve= 0 ,0
Exp/Cntr(USF)=0,0
Exp/Cntr=0.3,0.1

Type RM Length L Ch R = 1 ,3385    ,190.5,198,211.1
XS GIS Cut Line= 3
2152256.15639796 448376.014923862152525.56804395448187.727230754
2152616.70729966448167.696625104
#Sta/Elev= 30
       0 3287.21    11.9 3286.81    19.5 3285.63    39.4 3283.73    58.6 3283.19
    73.2 3281.92    78.1 3279.46    92.7 3270.18    97.6 3267.93   111.2 3267.23
   136.7 3267.15   144.6 3267.96   151.4 3269.49   175.7 3272.86   191.6 3273.91
   200.3 3275.43     205 3277.72   220.4 3286.69   248.9 3307.05   254.8 3312.62
   260.6 3317.28   268.4 3321.78   303.7 3331.58   312.3 3333.07   331.4 3337.86
   339.5 3338.76   343.6  3339.7     360 3345.02     401 3354.72     422 3360.66
#Mann= 4 ,-1,0
       0      .1       0    97.6    .045       0   144.6      .1       0
     310     .12       0
Bank Sta=97.6,144.6
XS Rating Curve= 0 ,0
Exp/Cntr(USF)=0,0
Exp/Cntr=0.3,0.1

Type RM Length L Ch R = 1 ,3187    ,159.3,165.9,177.1
XS GIS Cut Line= 2
 2152294.2145487448455.1358161772152634.73484474448471.160300696
#Sta/Elev= 30
       0 3277.15       6 3276.04      34 3276.23      50 3275.68      66 3273.76
      74 3272.11    86.1 3268.52    94.1  3268.2   106.1 3269.04   110.1 3268.33
   114.1 3266.38   118.1 3265.35     126 3264.76   146.1 3264.87   158.1  3261.4
   174.2 3261.15   182.2 3261.61   186.2 3264.22   198.9 3277.21   214.2 3293.71
   226.8 3303.25   238.2 3310.87   258.2 3320.23   282.3 3327.34   298.3 3334.65
     306 3338.65   310.3 3341.93   314.3 3344.22   334.3 3354.28   340.9 3358.44
#Mann= 3 ,-1,0
       0      .1       0   158.1    .045       0   182.2      .1       0
Bank Sta=158.1,182.2
XS Rating Curve= 0 ,0
Exp/Cntr(USF)=0,0
Exp/Cntr=0.3,0.1

Type RM Length L Ch R = 1 ,3021    ,89.2,99.9,112.3
XS GIS Cut Line= 2
2152269.17629164448528.2475267982152517.55580169 448686.48931143
#Sta/Elev= 30
       0 3282.66      13  3279.5    24.1 3277.56    41.5 3273.09    53.8 3270.72
    63.7 3269.35    86.9 3263.58    88.9  3263.2    95.6 3263.35   112.6 3261.18
   120.8 3259.52   130.3 3257.01   136.1 3256.26   143.2 3257.34   153.5 3258.58
   160.1 3260.72   169.6 3262.87   173.8 3264.69   176.7 3267.04   185.4 3275.01
   199.8 3285.35   202.8 3287.13   205.6 3289.91   208.5 3292.32   217.2 3297.94
   225.9 3302.59   240.4 3307.82   259.7 3312.21   278.1 3316.94   294.5 3322.36
#Mann= 3 ,-1,0
       0      .1       0   130.3    .045       0   143.2      .1       0
Bank Sta=130.3,143.2
XS Rating Curve= 0 ,0
Exp/Cntr(USF)=0,0
Exp/Cntr=0.3,0.1

Type RM Length L Ch R = 1 ,2921    ,161.7,138.4,125.4
XS GIS Cut Line= 4
2152247.10901338448562.5763634572152283.50687866448605.304292259
2152347.59877186448725.5754992562152430.68085564448766.720912177
#Sta/Elev= 30
       0  3286.9    19.2 3285.23    29.7 3282.01    40.2 3278.12    45.2 3275.75
    57.5 3267.95    65.1 3264.47    74.3 3259.69    86.1 3255.49    89.1 3254.83
    96.8 3254.04   109.8 3254.59   119.4 3253.82   137.6 3253.42   154.1 3253.53
   159.6 3253.99   168.9 3254.51   171.8  3255.7   174.8 3257.42   182.9 3264.35
   186.6 3266.17     192 3267.67   219.8 3272.36   228.8 3276.16   237.7 3278.37
   242.2 3279.99   255.5 3286.43   264.5 3288.14   277.9 3292.37   285.1 3295.08
#Mann= 3 ,-1,0
       0      .1       0   119.4    .045       0   159.6      .1       0
Bank Sta=119.4,159.6
XS Rating Curve= 0 ,0
Exp/Cntr(USF)=0,0
Exp/Cntr=0.3,0.1

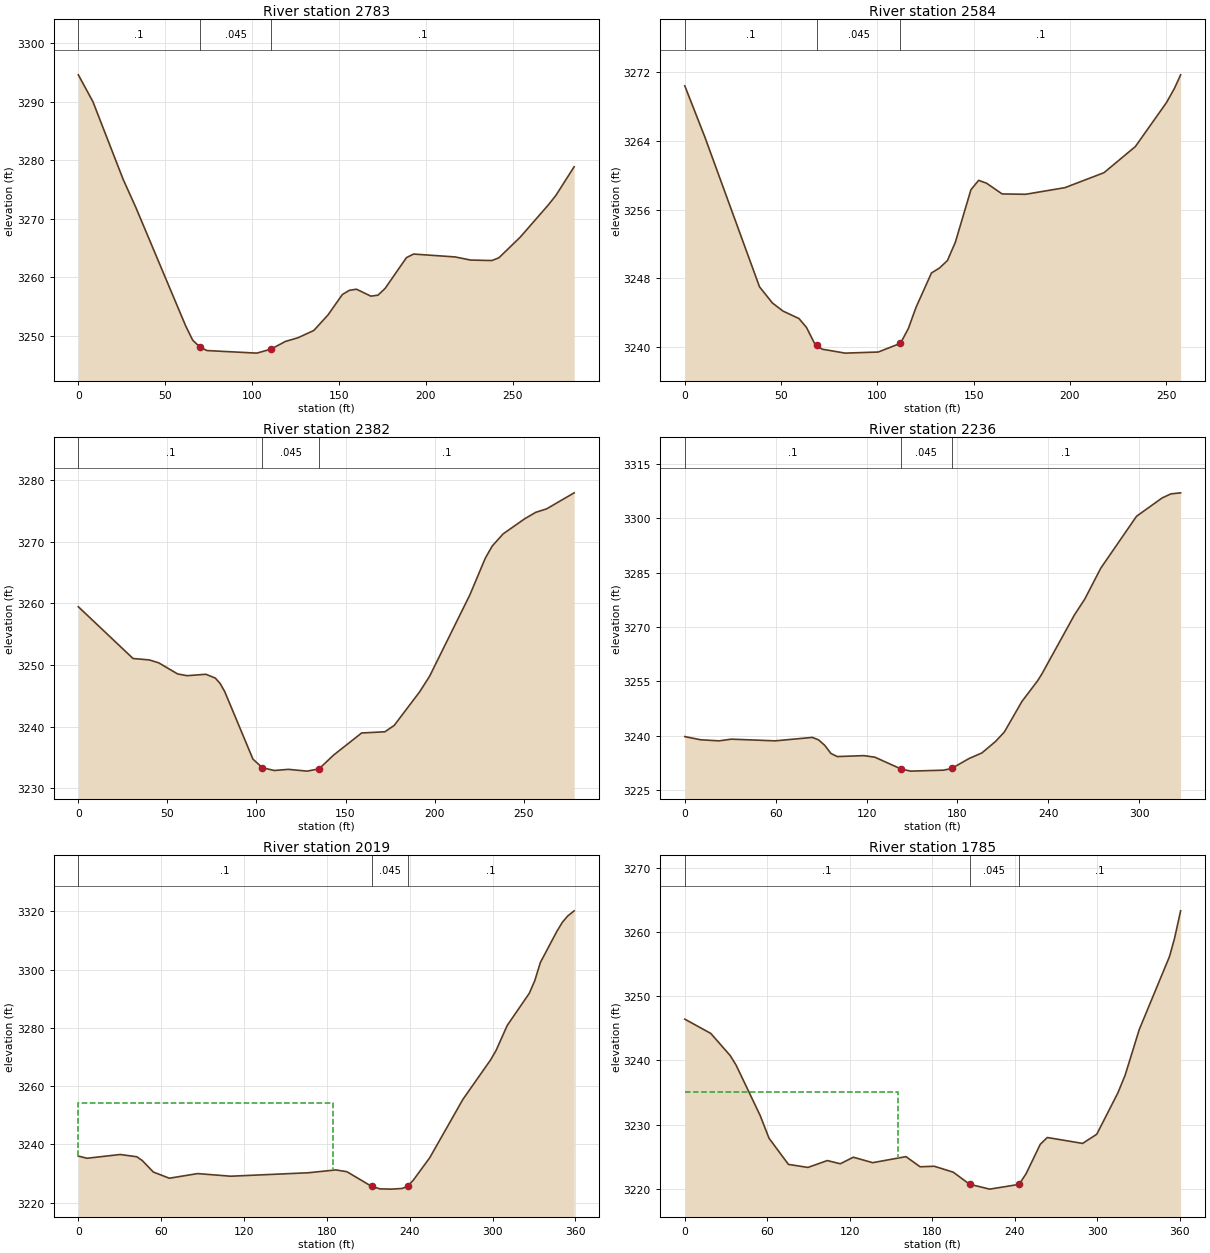
Type RM Length L Ch R = 1 ,2783    ,210.3,198.9,194.4
XS GIS Cut Line= 2
2152119.94827955448730.5566438592152398.37369808448792.651521373
#Sta/Elev= 30
       0 3294.57     8.4 3289.98    25.8  3276.7      33 3271.97    61.7 3251.71
    65.8 3249.22    69.9 3248.07      74 3247.45   102.7 3247.01   110.9  3247.7
   119.1    3249   126.4 3249.64   135.5 3250.88   143.7 3253.55   151.9 3257.02
     156 3257.75   160.1 3257.93   168.3 3256.75   172.4 3256.91   176.5 3258.06
   188.8 3263.33   192.9 3263.94   216.8 3263.45   225.6 3262.92   237.9 3262.83
     242  3263.3   254.3 3266.84   270.5 3272.36   274.8 3273.97   285.3 3278.86
#Mann= 3 ,-1,0
       0      .1       0    69.9    .045       0   110.9      .1       0
Bank Sta=69.9,110.9
XS Rating Curve= 0 ,0
Exp/Cntr(USF)=0,0
Exp/Cntr=0.3,0.1

Type RM Length L Ch R = 1 ,2584    ,213.4,201.8,189.3
XS GIS Cut Line= 2
2152145.98806689448959.9070785472152399.37522836448913.836685553
#Sta/Elev= 30
       0  3270.4    10.4 3264.46    38.8 3247.03    45.5 3245.15      51 3244.21
    59.3 3243.34    63.2 3242.31    67.3 3240.49    68.9 3240.21    71.3 3239.78
    83.3 3239.32   100.5 3239.45     112 3240.46   116.1 3242.18   120.1 3244.65
   128.1 3248.64   132.3 3249.22   136.4 3250.09   140.5 3252.21   148.6 3258.32
   152.6 3259.41   156.7 3259.08   164.8 3257.83     177 3257.79   197.4 3258.56
   217.7  3260.3     234 3263.34   250.2 3268.47   254.3 3270.11   257.5 3271.68
#Mann= 3 ,-1,0
       0      .1       0    68.9    .045       0     112      .1       0
Bank Sta=68.9,112
XS Rating Curve= 0 ,0
Exp/Cntr(USF)=0,0
Exp/Cntr=0.3,0.1

Type RM Length L Ch R = 1 ,2382    ,148.5,146.4,144.4
XS GIS Cut Line= 2
2152210.08600497449209.2881188852152420.40736429449027.009607474
#Sta/Elev= 30
       0 3259.46    30.7 3251.06    39.8 3250.83    45.1 3250.36    55.7 3248.56
      61 3248.27    71.6  3248.5    76.9 3247.88    79.6    3247    82.2 3245.67
      98 3234.73   103.3 3233.33   110.1 3232.88   117.8 3233.07   128.4 3232.78
   135.1 3233.15   143.3 3235.39     159 3238.97   172.1 3239.17   177.3  3240.2
   191.5 3245.62   197.2  3248.2   219.8 3261.41   228.4 3267.33   232.3 3269.31
   238.4 3271.28   250.6 3273.75   256.7 3274.78   262.8 3275.34   278.3 3277.95
#Mann= 3 ,-1,0
       0      .1       0   103.3    .045       0   135.1      .1       0
Bank Sta=103.3,135.1
XS Rating Curve= 0 ,0
Exp/Cntr(USF)=0,0
Exp/Cntr=0.3,0.1

Type RM Length L Ch R = 1 ,2236    ,196.9,216.8,231.5
XS GIS Cut Line= 3
2152266.17170079449288.4090112022152377.34156214449262.369223857
2152524.56651367449108.133560355
#Sta/Elev= 30
       0 3239.82    10.3 3238.95    22.6 3238.64    30.8 3239.11    59.6 3238.64
    84.2 3239.59    88.3 3238.93    92.4 3237.41    96.5 3235.17   100.7 3234.31
   118.3 3234.57   125.5 3234.14   142.5 3230.95     149  3230.3   170.8 3230.56
   176.2 3231.03   187.7 3233.77   196.2 3235.32   205.2 3238.48     211 3241.08
   222.6 3249.49     233 3255.22   235.9 3257.16   257.3 3273.36   264.1  3277.7
   274.7 3286.24   298.3 3300.54   315.2 3305.58     321  3306.7   327.4 3306.99
#Mann= 3 ,-1,0
       0      .1       0   142.5    .045       0   176.2      .1       0
Bank Sta=142.5,176.2
XS Rating Curve= 0 ,0
Exp/Cntr(USF)=0,0
Exp/Cntr=0.3,0.1

Type RM Length L Ch R = 1 ,2019    ,218.7,233.5,246.9
XS GIS Cut Line= 2
2152285.90244855449405.8639466132152644.68418049449421.720424885
#Sta/Elev= 30
       0 3236.02     6.3 3235.26    30.3 3236.55    42.3 3235.78    46.3 3234.49
    54.3 3230.54    65.9 3228.41    86.4    3230   110.4  3229.1   166.5 3230.28
   186.5 3231.26   194.5 3230.65   212.4 3225.62   218.5 3224.75   226.5 3224.67
   234.5 3224.89   238.5 3225.67   242.5 3227.68   254.5 3235.44   278.5 3255.45
   298.6 3269.02   302.6  3272.3   310.6 3280.81   326.6 3291.85   330.6 3296.22
   334.6 3302.39   346.6 3313.13   350.6 3316.24   354.3 3318.32   359.1 3320.15
#Mann= 3 ,-1,0
       0      .1       0   212.4    .045       0   238.5      .1       0
#XS Ineff= 2 , 0
          184.33 3254.25
Permanent Ineff=
       F       F
Bank Sta=212.4,238.5
XS Rating Curve= 0 ,0
Exp/Cntr(USF)=0,0
Exp/Cntr=0.3,0.1

Type RM Length L Ch R = 1 ,1785    ,184.3,192,202.9
XS GIS Cut Line= 3
2152248.14415571  449505.74108252152378.34309243449586.865035381
2152539.58946791449717.063972104
#Sta/Elev= 30
       0 3246.43    18.9 3244.21      33 3240.77    37.4 3239.24    54.8 3231.44
    61.3 3227.88    75.4 3223.81    89.6 3223.34   103.7 3224.41   113.1 3223.91
   122.6 3224.93   136.7 3224.08   160.9 3225.02   171.2 3223.44   181.5 3223.52
   195.3  3222.6   207.2 3220.72   221.8 3219.96   243.2  3220.7   248.3 3222.37
   258.6 3226.94   263.7    3228   289.4 3227.08   299.7 3228.51   315.1 3234.97
   320.3 3237.68   330.6 3244.81   352.6 3256.18   356.3 3259.03   360.7  3263.3
#Mann= 3 ,-1,0
       0      .1       0   207.2    .045       0   243.2      .1       0
#XS Ineff= 2 , 0
          154.84 3235.08
Permanent Ineff=
       F       F
Bank Sta=207.2,243.2
XS Rating Curve= 0 ,0
Exp/Cntr(USF)=0,0
Exp/Cntr=0.3,0.1

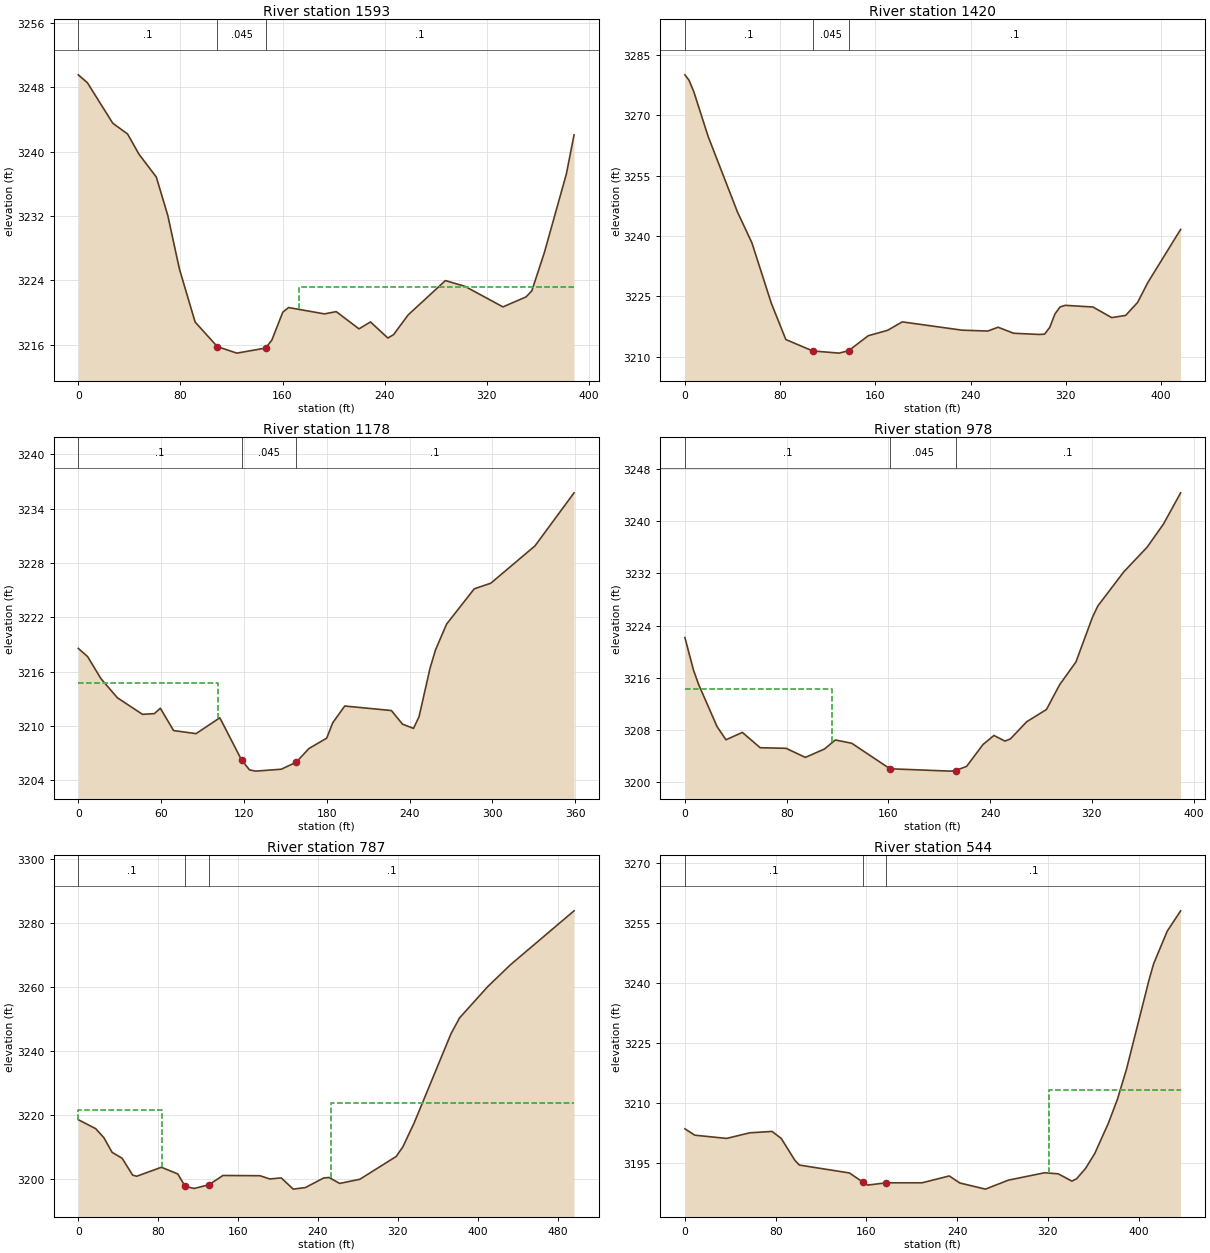
Type RM Length L Ch R = 1 ,1593    ,197.6,173.2,146.5
XS GIS Cut Line= 3
2152206.07988384449602.8895199012152293.21301842449771.146607358
2152469.48234813449863.287393346
#Sta/Elev= 30
       0 3249.55     7.1 3248.57      27 3243.53    38.6 3242.19    47.6 3239.66
    61.1 3236.84    70.1 3232.06    79.2 3225.41    91.5 3218.81   108.9 3215.75
   124.2 3214.94   146.7 3215.57   151.6 3216.55   160.2 3220.03   164.7 3220.61
   192.8 3219.82   202.1  3220.1   219.9 3217.96   228.9 3218.82   242.5 3216.82
     247 3217.24   258.4 3219.69   287.6 3223.96   302.9 3223.25   332.7 3220.69
   350.8 3221.93   355.3 3222.68   365.1 3227.42   382.4 3237.23   388.4 3242.08
#Mann= 3 ,-1,0
       0      .1       0   108.9    .045       0   146.7      .1       0
#XS Ineff= 2 , 0
                          173.27         3223.19
Permanent Ineff=
       F       F
Bank Sta=108.9,146.7
XS Rating Curve= 0 ,0
Exp/Cntr(USF)=0,0
Exp/Cntr=0.3,0.1

Type RM Length L Ch R = 1 ,1420    ,243.5,242.4,237.9
XS GIS Cut Line= 3
2152068.87023514449859.2812722162152275.18547333449820.221591199
  2152465.476227449900.344013798
#Sta/Elev= 30
       0 3280.11     3.4  3278.8     7.4 3275.97    19.6 3264.73    44.1 3246.05
    56.3 3238.34    72.6 3223.32    84.8  3214.3   107.3 3211.47   129.6 3210.92
   137.7 3211.55     154 3215.24   170.3 3216.59   182.6 3218.69   232.8 3216.63
   254.5 3216.41   263.1 3217.36   276.2 3215.86   297.9 3215.56   302.2 3215.64
   306.5  3217.3   310.9 3220.65   315.2 3222.41   319.6  3222.8   342.8 3222.39
   358.6 3219.75   370.3  3220.3   380.3 3223.51     389  3228.5   416.5 3241.68
#Mann= 3 ,-1,0
       0      .1       0   107.3    .045       0   137.7      .1       0
Bank Sta=107.3,137.7
XS Rating Curve= 0 ,0
Exp/Cntr(USF)=0,0
Exp/Cntr=0.3,0.1

Type RM Length L Ch R = 1 ,1178    ,200.6,200,199.4
XS GIS Cut Line= 3
2152128.96205209450115.6730245322152332.27269943450034.549071651
2152472.48693898450034.549071651
#Sta/Elev= 30
       0 3218.56     6.7 3217.66    16.4 3215.22    28.3 3213.11    46.5 3211.28
    55.1 3211.36    59.4 3211.96      69 3209.49    85.3 3209.15   102.5  3210.9
   118.3 3206.23     124 3205.15   128.4 3205.01     147 3205.22   157.8 3205.99
   167.1 3207.51   179.9 3208.65   184.3 3210.35     193  3212.2   226.8  3211.7
   234.8  3210.2   242.8 3209.73   246.8 3211.01   254.8 3216.38   258.8 3218.42
   266.8 3221.25   286.8 3225.14   298.8 3225.76   330.8 3229.88   359.1 3235.74
#Mann= 3 ,-1,0
       0      .1       0   118.3    .045       0   157.8      .1       0
#XS Ineff= 2 , 0
          101.22 3214.79
Permanent Ineff=
       F       F
Bank Sta=118.3,157.8
XS Rating Curve= 0 ,0
Exp/Cntr(USF)=0,0
Exp/Cntr=0.3,0.1

Type RM Length L Ch R = 1 ,978     ,186.4,191,199.7
XS GIS Cut Line= 2
2152150.17596894450319.9869374152152512.72993119 450176.76810702
#Sta/Elev= 30
       0 3222.15     6.8 3217.15    10.8 3214.97    25.3 3208.53    32.3 3206.52
    45.2 3207.64    59.2  3205.3    79.6 3205.21    94.7 3203.82   109.7  3205.1
   118.3 3206.49   131.2 3205.98   161.3 3202.08   208.6 3201.72   212.9 3201.81
   221.5 3202.45   234.4 3205.79     243 3207.18   251.6 3206.32   255.9 3206.64
   268.8 3209.28   284.3 3211.15   294.6 3214.92   307.5 3218.43   320.4 3225.23
   324.7 3226.99   345.1 3232.21   363.4 3235.97   376.3 3239.52   389.8  3244.3
#Mann= 3 ,-1,0
       0      .1       0   161.3    .045       0   212.9      .1       0
#XS Ineff= 2 , 0
          115.31 3214.35
Permanent Ineff=
       F       F
Bank Sta=161.3,212.9
XS Rating Curve= 0 ,0
Exp/Cntr(USF)=0,0
Exp/Cntr=0.3,0.1

Type RM Length L Ch R = 1 ,787     ,237.5,242.5,238
XS GIS Cut Line= 3
2152227.29380069450469.214949505 2152386.5371156 450431.15679877
2152636.51213879450211.703455925
#Sta/Elev= 30
       0 3218.61    17.4 3215.81    25.6 3212.99    33.8 3208.42    43.9 3206.55
    54.4 3201.29    58.5 3200.95    83.2 3203.75    99.6 3201.67     107 3197.76
   116.1 3197.13   130.8 3198.29   144.8 3201.18   181.9 3201.11   191.8 3200.09
   203.2 3200.43   215.2 3196.92   227.4 3197.41   245.7 3200.41   251.1 3200.55
   261.7  3198.7   281.9    3200   318.3 3207.12     325 3210.14   336.4 3217.68
   373.2 3245.48   381.7  3250.4     410  3260.2   432.7 3267.02   496.4 3283.87
#Mann= 3 ,-1,0
       0      .1       0     107    .045       0   130.8      .1       0
#XS Ineff= 2 , 0
           84.11 3221.54  252.69         3223.98
Permanent Ineff=
       F       F
Bank Sta=107,130.8
XS Rating Curve= 0 ,0
Exp/Cntr(USF)=0,0
Exp/Cntr=0.3,0.1

Type RM Length L Ch R = 1 ,544     ,192.8,206.8,219.1
XS GIS Cut Line= 3
2152347.47743459 450592.403174252152476.67484103 450584.39093199
2152783.93553136450568.370029232
#Sta/Elev= 30
       0 3203.53     8.7 3201.94    36.8 3201.13    57.1 3202.53    76.8 3202.88
    84.9 3201.14    96.9  3195.7   100.9 3194.48     145 3192.51     157 3190.22
     161 3189.48   177.7 3190.05   209.1 3190.05   233.1 3191.76   242.4    3190
     265 3188.47   285.2 3190.71   317.2 3192.56   329.2 3192.29   341.2 3190.47
   345.3 3191.04   353.2 3193.61   361.3 3197.32   373.3 3204.87   381.3 3210.84
   389.3 3218.34   409.3 3240.78   413.3 3244.75   425.3 3252.89   437.1 3257.96
#Mann= 3 ,-1,0
       0      .1       0     157    .045       0   177.7      .1       0
#XS Ineff= 2 , 0
                          321.04          3213.3
Permanent Ineff=
       F       F
Bank Sta=157,177.7
XS Rating Curve= 0 ,0
Exp/Cntr(USF)=0,0
Exp/Cntr=0.3,0.1

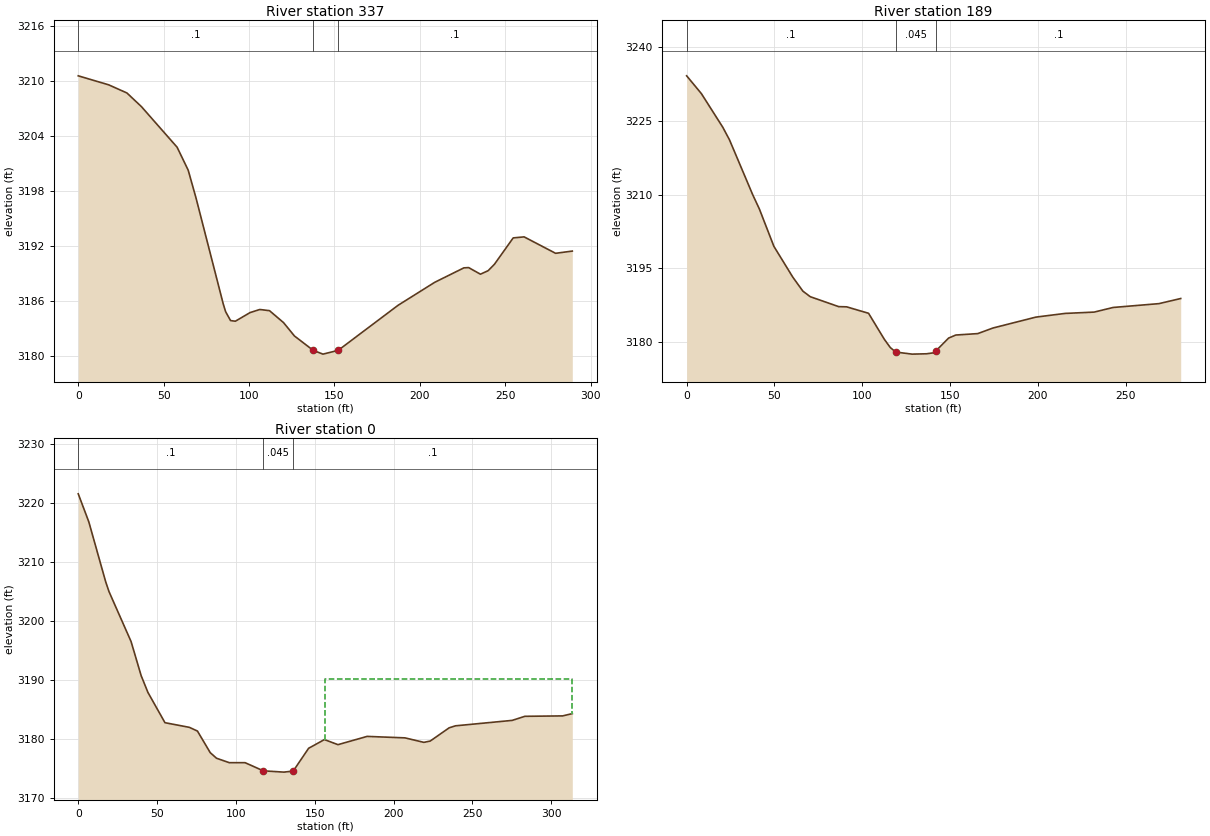
Type RM Length L Ch R = 1 ,337     ,153.1,148.5,142.8
XS GIS Cut Line= 2
2152321.91144085450670.0787202062152547.78349108 450850.79798713
#Sta/Elev= 30
       0 3210.56    17.8 3209.58    28.5 3208.69      37  3207.2    57.9 3202.77
    64.4 3200.26      69 3197.21    84.9 3185.68    86.3 3184.83    89.2 3183.86
      92 3183.79   100.6 3184.73   106.3 3185.07     112 3184.94   120.2 3183.64
   126.6 3182.18   137.6 3180.61   143.3  3180.2   152.2 3180.61   187.3 3185.53
   208.7 3188.03   225.8 3189.61   228.6 3189.64   235.5 3188.92     240  3189.3
   243.7    3190   254.7 3192.88   261.1 3192.99   279.5  3191.2   289.3 3191.44
#Mann= 3 ,-1,0
       0      .1       0   137.6    .045       0   152.2      .1       0
Bank Sta=137.6,152.2
XS Rating Curve= 0 ,0
Exp/Cntr(USF)=0,0
Exp/Cntr=0.3,0.1

Type RM Length L Ch R = 1 ,189     ,183.2,188.9,193.1
XS GIS Cut Line= 2
2152212.27084645450826.761260351  2152483.685553450900.874501255
#Sta/Elev= 30
       0 3234.12     8.4  3230.5    20.6 3223.66    24.4 3221.11    37.7  3209.9
    41.4 3207.08    49.7 3199.46    60.5 3193.19    66.2 3190.37    70.4 3189.24
    86.6 3187.22    91.1 3187.18   103.6 3185.87   112.6 3180.58     116  3178.9
   119.1 3177.99   128.4 3177.57   136.7 3177.64   140.9 3177.85   141.9  3178.2
   149.2 3180.83   153.3 3181.45   165.8 3181.74   174.5 3182.88   198.9 3185.09
   215.5 3185.84   232.1 3186.11   242.9 3187.05     269 3187.83   281.4 3188.87
#Mann= 3 ,-1,0
       0      .1       0   119.1    .045       0   141.9      .1       0
Bank Sta=119.1,141.9
XS Rating Curve= 0 ,0
Exp/Cntr(USF)=0,0
Exp/Cntr=0.3,0.1

Type RM Length L Ch R = 1 ,0       ,,,
XS GIS Cut Line= 4
2152171.21439162450950.591787968 2152218.3975591 450992.81290877
2152303.82807031451058.1220802362152446.23886407451060.249932206
#Sta/Elev= 30
       0 3221.48     6.7 3216.74    17.4 3206.59    19.5 3204.93    33.5 3196.47
    39.9 3190.69    44.2 3187.85      55 3182.73    70.5 3181.94    75.6 3181.31
    83.7 3177.66    87.7 3176.71    95.8 3175.96   105.8 3175.96117.40123174.578
   130.5 3174.36136.32483174.545   146.1  3178.4   156.1 3179.87   164.7 3179.01
   183.2 3180.41   207.2 3180.16   219.2  3179.4   223.2 3179.62   235.2 3181.86
   239.2  3182.2   275.2 3183.12   283.2 3183.81   307.2 3183.88   313.3 3184.27
#Mann= 3 ,-1,0
       0      .1       0117.4012    .045       0136.3248      .1       0
#XS Ineff= 2 , 0
                          156.17         3190.17
Permanent Ineff=
       F       F
Bank Sta=117.4012,136.3248
XS Rating Curve= 0 ,0
Exp/Cntr(USF)=0,0
Exp/Cntr=0.3,0.1
LCMann Table=0

Chan Stop Cuts=-1
Use User Specified Reach Order=0
Composite Channel Slope=5